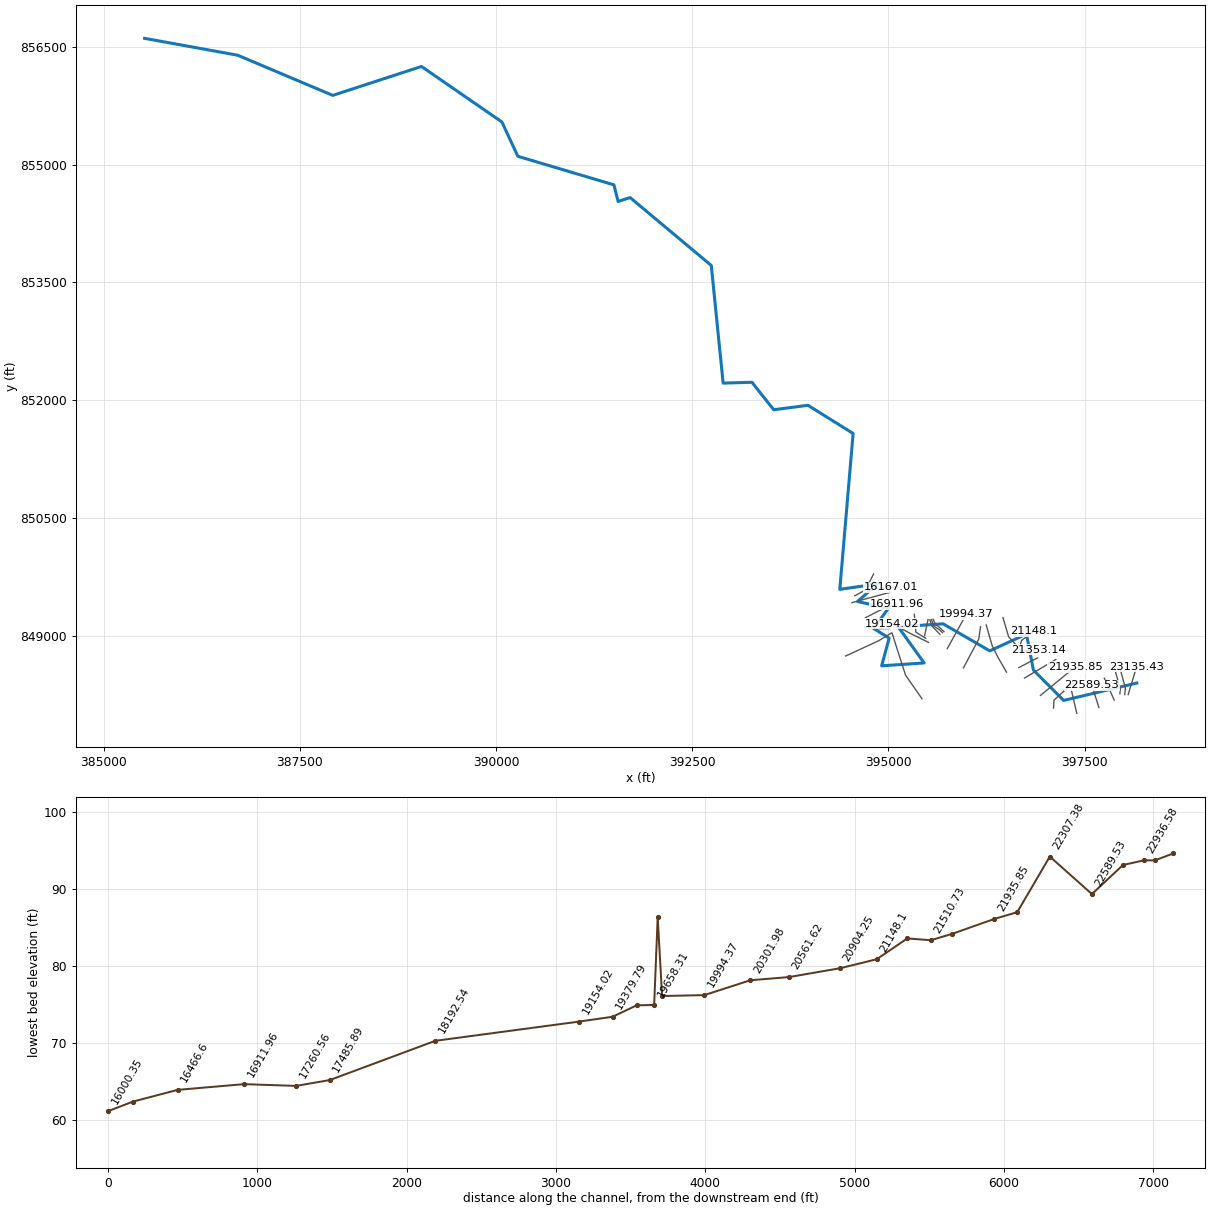
--- 6959_ras.prj (project) ---

Proj Title=6959
Current Plan=p01
Default Exp/Contr=0.3,0.1
English Units
Geom File=g01
Flow File=f01
Plan File=p01
Y Axis Title=Elevation
X Axis Title(PF)=Main Channel Distance
X Axis Title(XS)=Station
BEGIN DESCRIPTION:
RFD model 6959 exported to HEC-RAS
END DESCRIPTION:

--- 6959_ras.p01 (plan) ---

Plan Title=Plan 01
Program Version=4.10
Short Identifier=Plan 01
Geom File=g01
Flow File=f01
Subcritical Flow
Calc Critical at every XS
Secant Critical Depth

--- 6959_ras.f01 (steady flow) ---

Flow Title=Flow 01
Program Version=5.01
Number of Profiles= 6
Profile Names=10yr,25yr,50yr,100yr,100plus,500yr
River Rch & RM=6959,65,23135.43
 1792.82 2823.37 3779.93 4622.37 6748.65 8212.11
River Rch & RM=6959,65,22936.58
  1797.2 2830.43 3789.54 4634.28 6766.05 8230.89
River Rch & RM=6959,65, 22797.4
 1799.77 2834.59  3795.2 4641.29 6776.28 8241.93
River Rch & RM=6959,65,22589.53
 1801.84 2837.92 3799.73  4646.9 6784.48 8250.76
River Rch & RM=6959,65,22307.38
 1807.81 2847.52 3812.78 4663.05 6808.06 8276.12
River Rch & RM=6959,65,22089.69
 1813.77 2857.12 3825.83  4679.2 6831.63 8301.45
River Rch & RM=6959,65,21935.85
  1878.1 2960.89 3967.03 4854.16 7087.07 8575.91
River Rch & RM=6959,65,21654.62
 1880.88 2965.39 3973.17 4861.77 7098.19 8587.86
River Rch & RM=6959,65,21510.73
 1883.67 2969.89  3979.3 4869.38  7109.3  8599.8
River Rch & RM=6959,65,21353.14
 1884.17 2970.71 3980.42 4870.77 7111.32 8601.97
River Rch & RM=6959,65, 21148.1
 1894.32 2987.11 4002.75 4898.46 7151.75 8645.34
River Rch & RM=6959,65,20904.25
  1897.1  2991.6 4008.88 4906.06 7162.85 8657.25
River Rch & RM=6959,65,20561.62
 1906.44  3006.7 4029.45 4931.59 7200.12 8697.27
River Rch & RM=6959,65,20301.98
 1930.19 3045.08 4081.73 4996.43 7294.79 8798.61
River Rch & RM=6959,65,19994.37
 1944.97    3069 4114.35 5036.93 7353.92 8861.98
River Rch & RM=6959,65, 19711.4
 1951.46 3079.52  4128.7 5054.75 7379.94 8889.85
River Rch & RM=6959,65,19540.97
  1952.2 3080.71 4130.35  5056.8 7382.92 8893.07
River Rch & RM=6959,65,19379.79
 1955.64 3086.31    4138 5066.32 7396.83 8908.06
River Rch & RM=6959,65,19154.02
 1958.09  3090.3 4143.46 5073.13 7406.77 8918.76
River Rch & RM=6959,65,18192.54
 1967.18 3105.08 4163.68 5098.29  7443.5 8958.32
River Rch & RM=6959,65,17485.89
 2590.78 4106.75 5523.43 6779.01 9897.36 11497.7
River Rch & RM=6959,65,16911.96
 2594.47 4112.76 5531.66 6789.27 9912.3311513.19
River Rch & RM=6959,65, 16466.6
  2598.6 4119.49  5540.9 6800.78 9929.1411530.61
River Rch & RM=6959,65,16167.01
 2596.31 4115.76 5535.78 6794.39 9919.8111520.93
River Rch & RM=6959,65,16000.35
  2598.6 4119.49  5540.9 6800.78 9929.1411530.61
River Rch & RM=6959,65,15810.85
 2601.34 4123.97 5547.04 6808.44 9940.3311542.21
River Rch & RM=6959,65,15583.55
  2619.6 4153.89 5588.17 6859.8510015.3811620.43
River Rch & RM=6959,65,15260.24
 2621.41 4156.85 5592.24 6864.93 10022.811628.14
River Rch & RM=6959,65, 15023.7
 2623.89 4160.92 5597.83 6871.91   1003311638.75
River Rch & RM=6959,65,14879.27
 2625.26 4163.15 5600.89 6875.7310038.5711644.53
River Rch & RM=6959,65,14698.88
 2627.07 4166.12 5604.96 6880.8210045.9911652.24
River Rch & RM=6959,65,14487.66
 2628.43 4168.34 5608.02 6884.6310051.5611658.01
River Rch & RM=6959,65,14285.61
 2893.46  4605.4 6211.32 7641.3811156.42 12809.2
River Rch & RM=6959,65,14033.23
  2897.9 4612.65 6221.28 7653.8211174.5712827.75
River Rch & RM=6959,65,13638.99
 2903.58 4621.98 6234.13 7669.8911198.0412851.86
River Rch & RM=6959,65,13182.22
 3013.59  4801.1 6479.48 7975.5111644.2413303.89
River Rch & RM=6959,65,12725.45
 3023.71 4817.85 6502.64 8004.6211686.7413347.75
River Rch & RM=6959,65,12358.39
 3028.25  4825.4 6513.13 8017.8411706.0513367.84
River Rch & RM=6959,65,11713.51
 3036.79 4839.67    6533 8042.9511742.7113406.15
River Rch & RM=6959,65, 11053.4
 3092.74 4933.31 6663.45 8207.8911983.5213657.77
River Rch & RM=6959,65,10932.16
 3095.12 4937.31 6669.04 8214.9711993.8613668.62
River Rch & RM=6959,65,10312.99
 3104.55 4953.22 6691.29 8243.22 12035.113712.03
River Rch & RM=6959,65,9838.042
 3143.84 5018.82 6782.58 8358.5112203.42 13886.9
River Rch & RM=6959,65, 9363.09
 3149.57 5028.45 6796.03 8375.5612228.3213912.96
River Rch & RM=6959,65,8888.137
 3156.05 5039.47 6811.52  8395.312257.14 13943.5
River Rch & RM=6959,65,8413.185
 3159.99 5046.19    6821 8407.4212274.8313962.34
River Rch & RM=6959,65,7938.232
 3164.12 5053.24 6830.93 8420.1112293.3613982.08
River Rch & RM=6959,65,7463.279
 3168.05 5059.96 6840.41 8432.2112311.0314000.91
River Rch & RM=6959,65,7234.709
 3168.61 5060.92 6841.76 8433.9412313.55 14003.6
River Rch & RM=6959,65,6315.861
 3744.75 6016.98 8167.2810102.7614750.0416475.84
River Rch & RM=6959,65,6048.321
 3758.47 6040.67 8200.9210145.9914813.1516542.21
River Rch & RM=6959,65,5937.819
 3759.34 6042.17 8203.0410148.7214817.1416546.41
River Rch & RM=6959,65,5390.968
 3767.87 6056.97 8224.13 10175.914856.8116588.36
River Rch & RM=6959,65, 4744.73
  3775.4 6070.21 8243.1310200.5314892.7716626.91
River Rch & RM=6959,65,3708.078
 3794.91 6104.58  8292.5 10264.614986.3216727.32
River Rch & RM=6959,65,2647.275
 3804.25 6121.26 8316.6510296.1515032.3816777.44
River Rch & RM=6959,65,1862.295
  4276.7 6935.16 9471.3811779.4117197.9419023.94
Boundary for River Rch & Prof#=6959,65,1
Up Type= 0
Dn Type= 2
Boundary for River Rch & Prof#=6959,65,2
Up Type= 0
Dn Type= 2
Boundary for River Rch & Prof#=6959,65,2
Up Type= 0
Dn Type= 2
Boundary for River Rch & Prof#=6959,65,2
Up Type= 0
Dn Type= 2
Boundary for River Rch & Prof#=6959,65,2
Up Type= 0
Dn Type= 2
Boundary for River Rch & Prof#=6959,65,2
Up Type= 0
Dn Type= 2

--- 6959_ras.g01 (geometry) ---

Geom Title=6959
Program Version=4.10

River Reach=6959,65
Reach XY= 30
398163.861350179848395.855122969 397232.90070191848173.893317416
396847.484035254848560.612067446396758.942368448849020.247484088
396291.494451791848805.403734073395696.442368478849150.455817416
395124.393757373849111.827345222395455.339937896848651.757900774
394913.890285105 848614.86553967395009.550007343 848968.16415076
394811.633340806849090.559984088395000.435424089849348.372484103
394605.904174268849434.309984103   394859.810424849658.268317431
394380.643757343849589.257900745   394550.435424851575.282206297
393974.914590657851934.657206342   393538.716674 851877.36553967
   393261.372924852227.625956312392894.185424268852217.209289655
392743.056951791853715.889845192   391709.029174854581.167623013
391556.251396269854531.167623013   391502.779174854742.973178551
 390278.59225297855106.775261864390075.554058284855544.275261879
   389050.814475856251.306511849387920.381170541855882.853459224
386709.149315447856394.622478411385523.107431799856609.811343282

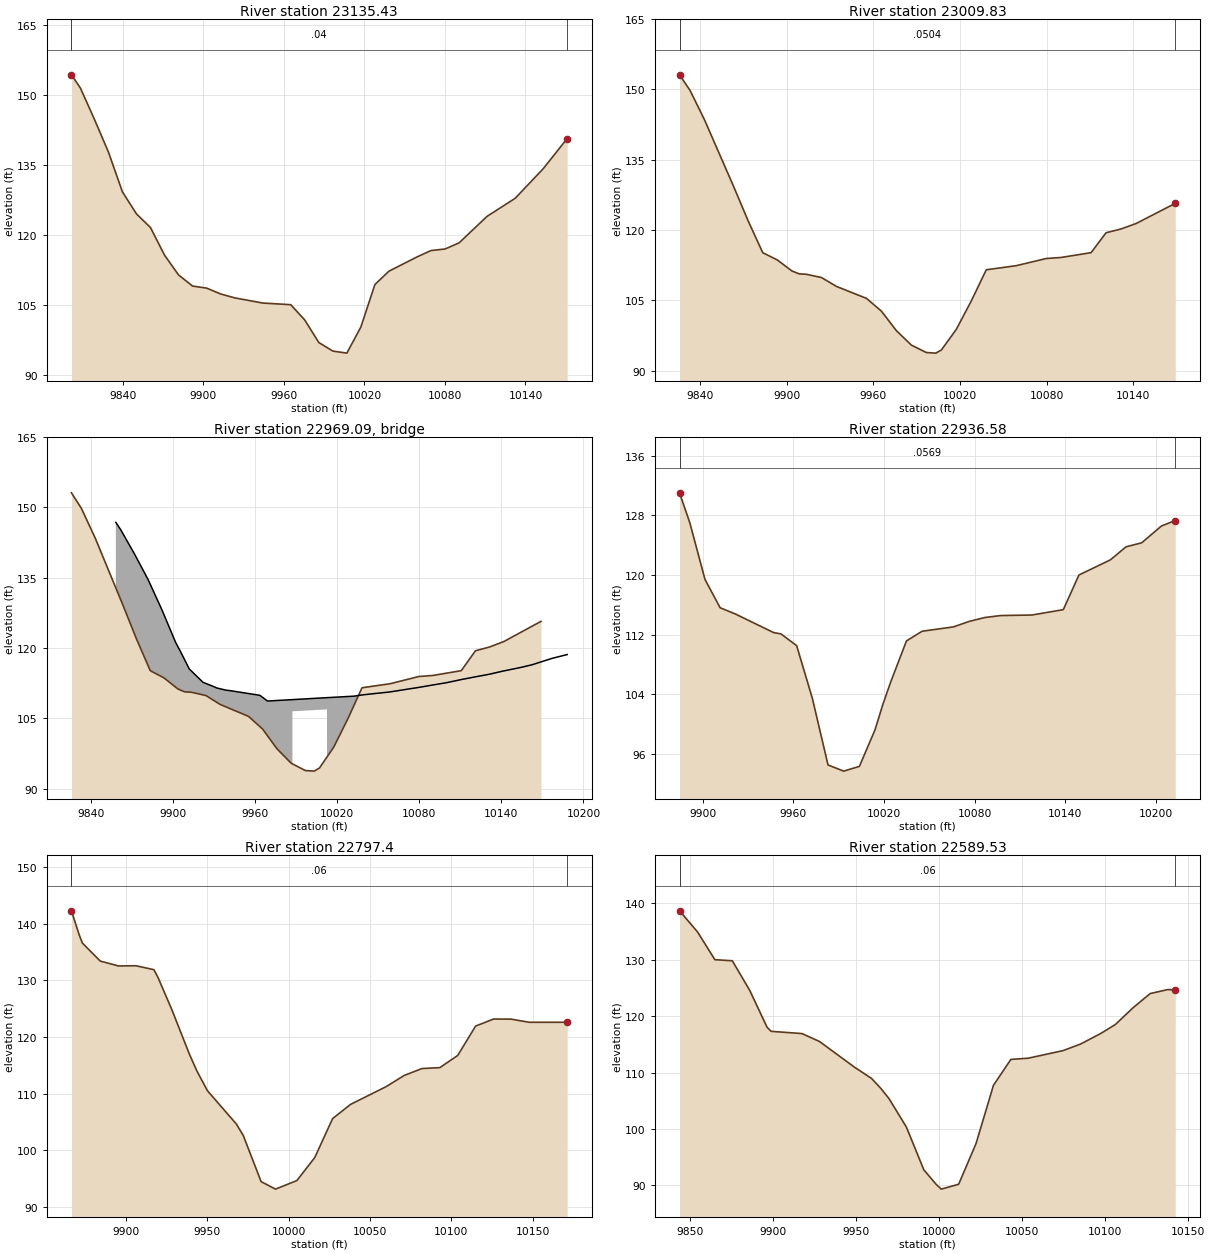
Type RM Length L Ch R = 1 ,23135.43,125.603800,125.603800,125.603800
XS GIS Cut Line= 2
 398055.19168103848248.634911653398162.118023533848602.080251686
#Sta/Elev= 30
9801.773154.34579808.423151.51959818.871144.80779829.318137.77619839.766129.2184
9850.213124.50359860.661121.56879871.109115.65059881.556111.40379892.004109.0183
9902.451 108.5779912.899107.32339923.347 106.4869944.242105.37739965.137105.0172
9975.585101.72939986.03296.90192 9996.4895.0684710006.9394.6254210017.37100.2336
10027.82 109.34310038.27112.210210059.17115.265210069.61116.635710080.06116.9691
10090.51118.2817 10111.4123.9786 10132.3127.845510153.19134.194210171.04 140.669
#Mann= 3 , 0 , 0
9801.773    0.04       09801.773    0.04       010171.04    0.04       0
#XS Ineff= 2 , 0
       0 9908.82        10069.09       0
Bank Sta=9801.773,10171.04
Exp/Cntr=0.3,0.1

Type RM Length L Ch R = 1 ,23009.83,73.251600,73.251600,73.251600
XS GIS Cut Line= 3
398010.553220482848247.773697061398019.868890312848329.994608639
397951.436801464848581.201010557
#Sta/Elev= 30
9825.898153.12429833.171 149.8049843.234143.48619863.362129.26669873.426 121.923
 9883.49115.15989893.554113.61129903.618111.26849908.645110.63669913.833110.5405
9924.197109.84379934.562107.9489 9955.29105.40239965.655 102.6729976.01998.50488
9986.38495.423629996.74893.8423210003.2693.7158710007.1194.3731910017.48 98.7956
10027.84104.857810038.21111.508810058.93112.381410079.66113.908610090.03114.1373
10110.76115.165110121.12 119.41110131.49120.220410141.85121.373310169.01125.6873
#Mann= 3 , 0 , 0
9825.898  0.0504       09825.898  0.0504       010169.01  0.0504       0
#XS Ineff= 2 , 0
       09940.668                       0
Bank Sta=9825.898,10169.01
Exp/Cntr=0.3,0.1

Type RM Length L Ch R = 3 ,22969.09,,,
BEGIN DESCRIPTION:
END DESCRIPTION:
Bridge Culvert--1,0,-1,-1, 0
Deck Dist Width WeirC Skew NumUp NumDn MinLoCord MaxHiCord MaxSubmerge Is_Ogee
24.486700,24.278200,2.6,0, 43, 43, , , 0.95, 0, 0,0,,
 9858.33 9861.76 9871.81 9881.85 9891.90 9901.95 9906.01 9912.00 9922.05 9930.55
 9932.16 9938.68 9942.63 9953.11 9963.58 9969.14 9987.37 9987.3710012.6310012.63
10032.3710036.8810039.8010047.3510057.8210068.2910073.5010078.7610089.2410099.71
10107.2110110.1810120.6510131.1210140.9110141.5910152.0610155.2510162.4710172.84
10176.9410183.2110188.13
  146.81  145.31  140.16  134.64  128.23  121.24  119.00  115.52  112.67  111.68
  111.46  111.01  110.86  110.38  109.90  108.68  108.98  108.98  109.40  109.40
  109.72  109.92  110.03  110.27  110.59  111.06  111.31  111.54  112.07  112.58
  113.04  113.23  113.82  114.39  115.05  115.09  115.72  115.92  116.42  117.39
  117.77  118.24  118.60
 -853.19 -854.69 -859.84 -865.36 -871.77 -878.76 -881.00 -884.48 -887.33 -888.32
 -888.54 -888.99 -889.14 -889.62 -890.10 -891.32 -891.02  106.48  106.90 -890.60
 -890.28 -890.08 -889.97 -889.73 -889.41 -888.94 -888.69 -888.46 -887.93 -887.42
 -886.96 -886.77 -886.18 -885.61 -884.95 -884.91 -884.28 -884.08 -883.58 -882.61
 -882.23 -881.76 -881.40
 9858.33 9861.76 9871.81 9881.85 9891.90 9901.95 9906.01 9912.00 9922.05 9930.55
 9932.16 9938.68 9942.63 9953.11 9963.58 9969.14 9987.37 9987.3710012.6310012.63
10032.3710036.8810039.8010047.3510057.8210068.2910073.5010078.7610089.2410099.71
10107.2110110.1810120.6510131.1210140.9110141.5910152.0610155.2510162.4710172.84
10176.9410183.2110188.13
  146.81  145.31  140.16  134.64  128.23  121.24  119.00  115.52  112.67  111.68
  111.46  111.01  110.86  110.38  109.90  108.68  108.98  108.98  109.40  109.40
  109.72  109.92  110.03  110.27  110.59  111.06  111.31  111.54  112.07  112.58
  113.04  113.23  113.82  114.39  115.05  115.09  115.72  115.92  116.42  117.39
  117.77  118.24  118.60
 -853.19 -854.69 -859.84 -865.36 -871.77 -878.76 -881.00 -884.48 -887.33 -888.32
 -888.54 -888.99 -889.14 -889.62 -890.10 -891.32 -891.02  106.48  106.90 -890.60
 -890.28 -890.08 -889.97 -889.73 -889.41 -888.94 -888.69 -888.46 -887.93 -887.42
 -886.96 -886.77 -886.18 -885.61 -884.95 -884.91 -884.28 -884.08 -883.58 -882.61
 -882.23 -881.76 -881.40
BR Coef=-1 , 0 , 0 ,, 0 ,,,0.8,0,1,0,
WSPro=,,,, 1 ,,,, 0 ,,,, 0 ,,,,-1 ,-1 ,-1 , 0 , 0 , 0 , 0 , 0
BC Design=,, 0 ,, 0 ,,,,,,

Type RM Length L Ch R = 1 ,22936.58,139.178700,139.178700,139.178700
XS GIS Cut Line= 3
397949.418700695848258.203444257397954.591112556848320.272386435
397882.507087499848576.382686944
#Sta/Elev= 30
9884.602131.01949891.422127.00189901.456 119.4179911.491115.61589921.526114.7872
9946.886112.29269951.797112.11059962.186110.53949972.574103.47749982.96394.54746
9993.35193.7201510003.7494.3565110014.1399.27898 10019.2102.616510024.52105.6904
10034.91111.169710045.29112.469410066.07113.051510076.46113.787210086.85114.3077
10097.24114.570810118.01114.642810138.79115.361210149.18120.008710169.96122.0322
10180.34123.779310190.73124.322510203.75126.565810211.51127.200910212.95127.1919
#Mann= 3 , 0 , 0
9884.602  0.0569       09884.602  0.0569       010212.95  0.0569       0
#XS Ineff= 2 , 0
       09961.575                       0
Bank Sta=9884.602,10212.95
Exp/Cntr=0.3,0.1

Type RM Length L Ch R = 1 , 22797.4,207.869700,207.869700,207.869700
XS GIS Cut Line= 2
397876.993340062848178.880021673397750.691256717848456.223771661
#Sta/Elev= 30
9866.415142.25169871.225137.9751 9873.14136.55759884.128133.37929895.353132.5184
9906.104132.55589917.092131.86069919.482130.5794 9928.08124.83789939.068116.8487
 9943.61113.93029950.057 110.4769967.739104.63519972.033102.59349983.02194.43954
9991.86793.11846   1000594.6306310015.9998.6928910026.97105.575110037.96108.0715
10059.94111.221310070.93113.181510081.91114.4071 10092.9114.569110103.89116.7235
10114.88121.903610125.87123.143610136.64123.131710147.84122.574310171.16122.5808
#Mann= 3 , 0 , 0
9866.415    0.06       09866.415    0.06       010171.16    0.06       0
#XS Ineff= 2 , 0
       0                               0
Bank Sta=9866.415,10171.16
Exp/Cntr=0.3,0.1

Type RM Length L Ch R = 1 ,22589.53,282.154400,282.154400,282.154400
XS GIS Cut Line= 2
397681.680840061848084.695993898397591.403062285848369.418216119
#Sta/Elev= 30
9843.521138.6948 9854.33  134.979864.821  130.039875.312 129.8449885.802124.5991
9896.293118.03699898.711117.32779917.274116.93139927.765115.53999948.746 111.012
9959.237108.96869964.883107.18319969.728 105.4029980.218100.35019990.70992.77301
9997.96990.25156 10001.289.3470610011.6990.2085810022.1897.4272710032.67 107.755
10043.16112.348210053.65112.562710074.63113.910410085.12115.064510097.23116.9311
10106.11118.5313 10116.6121.457910127.09124.023810137.58124.724610142.21124.6988
#Mann= 3 , 0 , 0
9843.521    0.06       09843.521    0.06       010142.21    0.06       0
#XS Ineff= 2 , 0
       0                               0
Bank Sta=9843.521,10142.21
Exp/Cntr=0.3,0.1

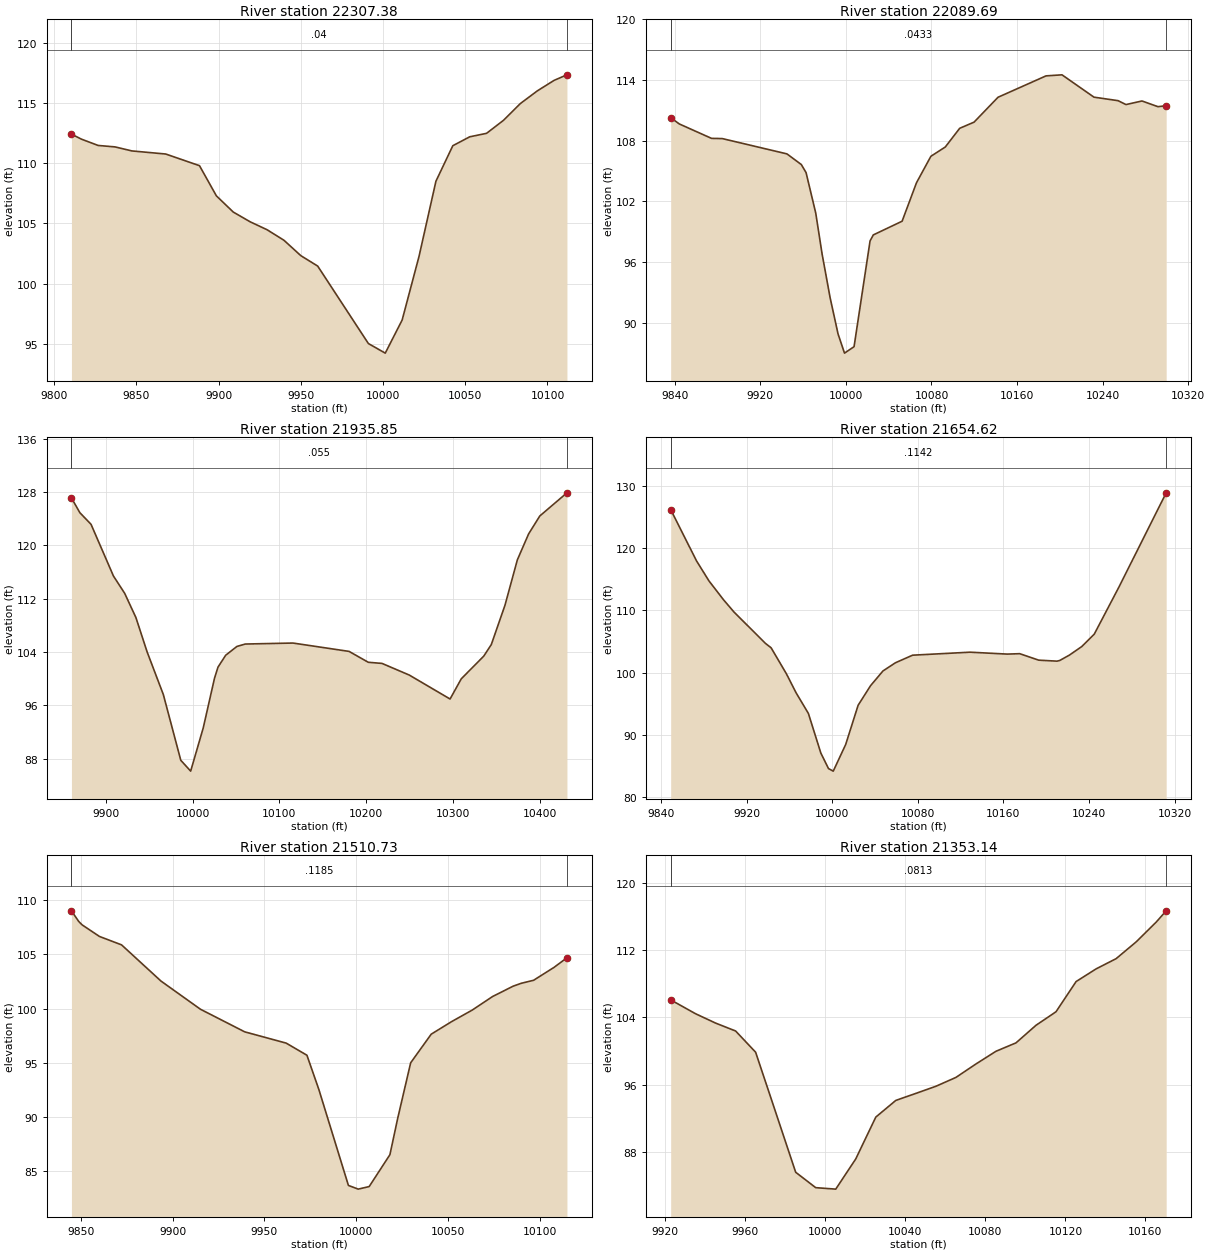
Type RM Length L Ch R = 1 ,22307.38,217.685100,217.685100,217.685100
XS GIS Cut Line= 2
397400.430840054848009.175160576397331.854451164848302.577938318
#Sta/Elev= 27
9810.525112.43459816.507112.01779826.776 111.4889837.046111.36869847.315111.0333
9867.854110.77669888.393109.80649898.663107.29749908.932105.94899919.202105.1387
9929.471 104.4799939.741103.6041 9950.01102.3234 9960.28101.45419991.08895.01356
10001.36 94.214810011.6396.96796 10021.9102.265810032.17108.512710042.44111.4671
10052.71112.207810062.97112.497510073.24113.577910083.51114.973310093.78 116.024
10104.05116.904310111.84117.3637
#Mann= 3 , 0 , 0
9810.525    0.04       09810.525    0.04       010111.84    0.04       0
#XS Ineff= 2 , 0
       0                               0
Bank Sta=9810.525,10111.84
Exp/Cntr=0.3,0.1

Type RM Length L Ch R = 1 ,22089.69,153.842600,153.842600,153.842600
XS GIS Cut Line= 3
397103.555840088848076.883493922397109.814619327848178.361644678
397378.446168383848420.138101493
#Sta/Elev= 30
9836.261110.28079844.393109.6575 9874.45108.23459884.469 108.2149944.908106.7009
9958.362105.64539962.803104.84429971.816100.85669977.75196.812899985.26992.47491
9992.69988.884679998.72386.9946710007.6587.63396 10022.698.0912710025.6398.68636
10052.54100.040310065.99 103.84510079.45106.4632 10092.9107.380610106.35109.2291
10119.81109.840910142.18112.300110187.03114.414810201.97114.519510231.87112.3102
10254.35111.964510261.77111.577310276.72 111.93310291.66111.368710299.34111.4618
#Mann= 3 , 0 , 0
9836.261  0.0433       09836.261  0.0433       010299.34  0.0433       0
#XS Ineff= 2 , 0
       0                10139.42       0
Bank Sta=9836.261,10299.34
Exp/Cntr=0.3,0.1

Type RM Length L Ch R = 1 ,21935.85,281.233000,281.233000,281.233000
XS GIS Cut Line= 2
 396937.52574747848237.748655953397379.180676732848600.351511252
#Sta/Elev= 30
9860.194127.13729869.865124.92039882.803123.1681 9908.68115.39779921.619112.8037
9934.557109.16889947.496 104.0059966.17797.610979986.31187.741939997.69686.11457
10012.1992.6012610025.13100.033410029.21101.728410038.07103.5095   10051 104.832
10060.73105.1958 10115.7105.342810180.39104.088710202.57102.453910218.33102.2876
10249.84100.534710296.8496.9410710309.7799.9734510335.65103.3726 10344.4105.1146
10360.16111.015410374.47117.842410387.41121.721810400.34124.421910431.63127.8959
#Mann= 3 , 0 , 0
9860.194   0.055       09860.194   0.055       010431.63   0.055       0
#XS Ineff= 2 , 0
       0                10109.87       0
Bank Sta=9860.194,10431.63
Exp/Cntr=0.3,0.1

Type RM Length L Ch R = 1 ,21654.62,143.885200,143.885200,143.885200
XS GIS Cut Line= 2
 396734.19820118848459.913007778397132.838247463 848695.64796148
#Sta/Elev= 30
9849.002126.16159873.168117.91859884.786114.70989898.288 111.7089908.021109.7452
 9937.58104.68529942.874103.97539957.22699.787169966.10996.788299977.72793.44081
9989.34587.090039996.51884.5944110000.9684.1871510012.5888.46299 10024.294.75445
10035.8197.8939810047.43100.260110059.05101.5732 10075.1102.789610128.76103.2713
10163.61102.965810175.23103.031710192.98101.992410210.08101.834510212.62101.9389
 10221.7102.805810233.31104.184810244.93106.172810268.17 113.78910312.13 128.842
#Mann= 3 , 0 , 0
9849.002  0.1142       09849.002  0.1142       010312.13  0.1142       0
#XS Ineff= 2 , 0
       0                10078.86       0
Bank Sta=9849.002,10312.13
Exp/Cntr=0.3,0.1

Type RM Length L Ch R = 1 ,21510.73,157.589400,157.589400,157.589400
XS GIS Cut Line= 3
396661.498548389848592.291480018396828.599242837 848680.18210499
396901.298895613848715.989396675
#Sta/Elev= 26
9844.942109.01069848.898108.0327 9850.76107.71649860.197106.64869872.242105.8721
9893.724102.53339915.20699.937459939.28997.855199961.88796.815279973.18695.69848
9979.65192.557369995.78483.6949410001.1383.3548410007.0883.5910710018.3886.52734
10022.6289.8778310029.6895.0003810040.8897.6397610052.0398.8024310063.1899.85716
10074.32101.113110085.47102.062410089.92102.331210096.62102.607510107.77103.7987
10114.79104.6817
#Mann= 3 , 0 , 0
9844.942  0.1185       09844.942  0.1185       010114.79  0.1185       0
#XS Ineff= 2 , 0
       0                10085.14       0
Bank Sta=9844.942,10114.79
Exp/Cntr=0.3,0.1

Type RM Length L Ch R = 1 ,21353.14,205.037700,205.037700,205.037700
XS GIS Cut Line= 2
 396662.58361784848804.965091113396909.979451179 848817.98592445
#Sta/Elev= 29
 9922.65106.01349923.314105.94569925.069 105.7629935.083104.43439945.097103.3223
9955.111102.38339965.12599.857349975.13992.730869985.15385.588779995.16683.75707
10005.1883.5825710015.1987.1748510025.2192.1468510035.2294.1299110045.2494.96358
10055.2595.8089410065.2696.8612310075.2898.4606510085.2999.97116 10095.3100.9692
10105.32103.062710113.58104.389110115.33104.677210125.35108.257810135.36109.7656
10145.37110.981710155.39112.9758 10165.4115.329110170.39116.6673
#Mann= 3 , 0 , 0
 9922.65  0.0813       0 9922.65  0.0813       010170.39  0.0813       0
#XS Ineff= 2 , 0
       0                               0
Bank Sta=9922.65,10170.39
Exp/Cntr=0.3,0.1

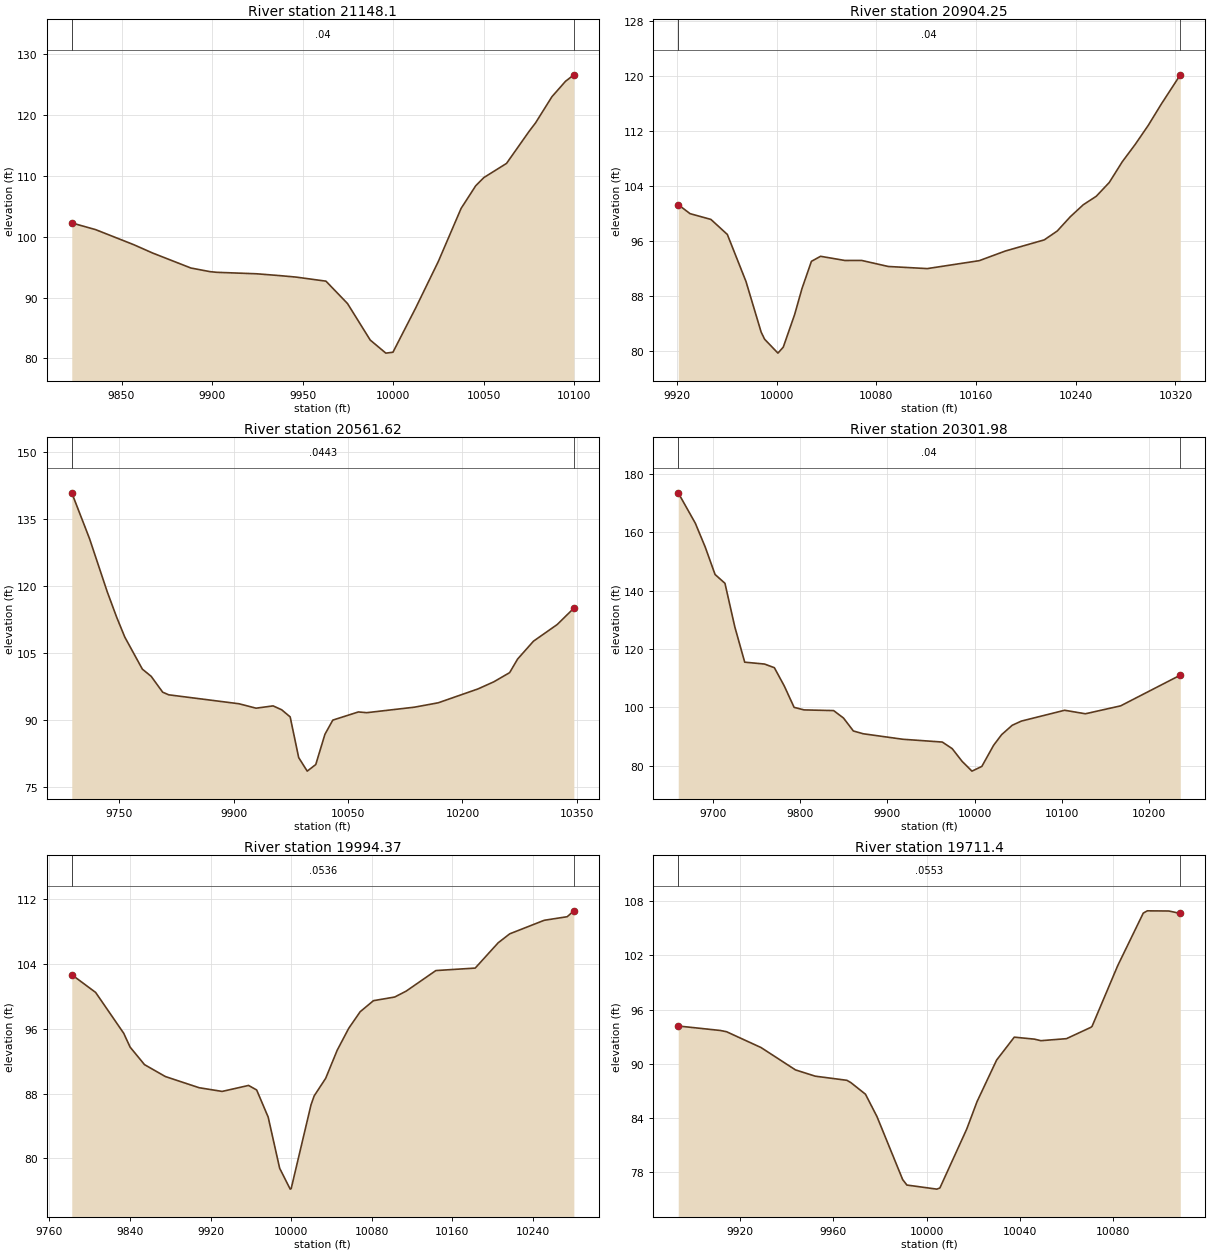
Type RM Length L Ch R = 1 , 21148.1,243.849500,243.849500,243.849500
XS GIS Cut Line= 3
396672.349242842848862.473771657396697.305840059 848938.42863277
396854.640909508849057.786271673
#Sta/Elev= 26
9822.489102.23769835.674101.13699856.72698.669939867.25297.288829888.303 94.8424
9898.82994.247739902.438 94.13899924.64893.89359  9937.293.600249946.40393.35428
9962.94892.684529974.85689.013319987.40883.02453 9996.04   80.889999.95981.02581
10012.5188.2812310025.0695.9274810037.62104.615710045.68108.326210050.17109.6705
10062.72     11210075.27117.287210078.77118.650910087.82122.943410095.31125.4679
10099.92126.5306
#Mann= 3 , 0 , 0
9822.489    0.04       09822.489    0.04       010099.92    0.04       0
#XS Ineff= 2 , 0
       0                               0
Bank Sta=9822.489,10099.92
Exp/Cntr=0.3,0.1

Type RM Length L Ch R = 1 ,20904.25,342.633100,342.633100,342.633100
XS GIS Cut Line= 3
396631.333617835848875.494605006396531.507228944848986.605716093
396459.458617851849229.661271666
#Sta/Elev= 30
9921.021101.29429930.49899.990459947.24399.152529960.42496.968679975.38790.13313
9987.57282.763829990.34981.7368810001.0279.7199810005.3180.5941410014.4685.34684
10020.2889.08209 10027.9 93.061510035.2493.7931710054.7993.1836810068.23  93.189
10089.5892.3128110120.8792.0043310162.59 93.158910183.4594.5565110214.7496.17967
10225.17 97.4705 10235.699.5370410246.03101.281810256.46102.516710266.89104.5184
10277.32107.530810287.75110.063810298.18112.821110308.61115.9038 10323.9120.1658
#Mann= 3 , 0 , 0
9921.021    0.04       09921.021    0.04       0 10323.9    0.04       0
#XS Ineff= 2 , 0
       0                 10078.5       0
Bank Sta=9921.021,10323.9
Exp/Cntr=0.3,0.1

Type RM Length L Ch R = 1 ,20561.62,259.638900,259.638900,259.638900
XS GIS Cut Line= 4
396504.196874967848534.672289447396396.090562278848723.584882828
396321.437784491848872.890438331396245.916951173849135.911271682
#Sta/Elev= 30
9687.788140.78429711.209130.48249734.252118.68379746.572113.01199757.295108.5412
9780.339101.3674 9791.8699.767119806.97396.217799814.90495.628219907.02893.63039
9929.38992.63948 9951.7593.15189 9962.9392.28814 9974.11 90.69569985.29181.59216
9996.47178.5686810007.6580.0380910019.6986.7978810030.0189.9732410063.5591.79971
10074.5791.6354910136.9992.8626210168.2193.8437310220.2396.9368410241.0398.52859
10261.84100.585710272.25103.614510293.05107.612110324.27 111.34910346.02114.9934
#Mann= 3 , 0 , 0
9687.788  0.0443       09687.788  0.0443       010346.02  0.0443       0
#XS Ineff= 2 , 0
       0                               0
Bank Sta=9687.788,10346.02
Exp/Cntr=0.3,0.1

Type RM Length L Ch R = 1 ,20301.98,307.617100,307.617100,307.617100
XS GIS Cut Line= 3
395955.538180699848587.706652257396151.515909512848956.874813413
396173.612010806849112.714853937
#Sta/Elev= 30
 9660.25 173.4739679.829163.05969691.151154.92079702.473145.49759713.794142.4846
9725.116127.52789736.438115.46799759.081114.83169770.403113.58149781.725107.3404
9793.04699.994919804.36899.124979838.33398.885269849.65596.331469860.97791.90222
9872.29990.947349917.58589.069469962.87288.111389974.19485.858689985.51681.51808
9996.83878.1532210008.1679.7661110021.6687.00328 10030.890.6330810042.9993.85982
10053.4595.2900510103.0399.0006610126.8297.7994110167.22100.506510235.61111.0291
#Mann= 3 , 0 , 0
 9660.25    0.04       0 9660.25    0.04       010235.61    0.04       0
#XS Ineff= 2 , 0
       0                               0
Bank Sta=9660.25,10235.61
Exp/Cntr=0.3,0.1

Type RM Length L Ch R = 1 ,19994.37,282.967900,282.967900,282.967900
XS GIS Cut Line= 2
395750.040215078848834.261966124395991.302527316849270.739764565
#Sta/Elev= 30
9782.142102.62529805.837100.44629833.73795.415639840.11593.707859854.40891.55303
9875.07990.089269908.671 88.71049931.52388.256929957.76488.993689965.80188.43401
9977.22785.099619988.65378.791279999.10676.2256210000.0876.2879610019.7886.60201
10022.9387.7070610034.3689.8713710045.7893.3233910057.2196.0174210068.6398.06976
10081.7999.4301510102.9199.8782110114.34100.6076 10143.8103.137410182.89103.4429
10205.75106.563310217.17107.659510251.45109.3284 10274.3109.768410280.86110.4925
#Mann= 3 , 0 , 0
9782.142  0.0536       09782.142  0.0536       010280.86  0.0536       0
#XS Ineff= 2 , 0
       0                               0
Bank Sta=9782.142,10280.86
Exp/Cntr=0.3,0.1

Type RM Length L Ch R = 1 , 19711.4,29.537400,29.537400,29.537400
XS GIS Cut Line= 4
 395708.27764215849050.964500441395653.747477879 849101.06628504
395598.018311178849145.857951784395569.155482175849209.468963247
#Sta/Elev= 28
9893.40294.180139911.43393.684819914.14793.543289928.927 91.79239943.707 89.3163
9952.17388.621199965.75388.163499967.45487.910149973.73386.623349978.67784.13768
9989.69577.164569991.50676.5577410004.3476.1065510005.6676.2361210017.1782.75782
10021.6285.81286   1003090.4066410037.5892.9438510046.2692.7231810048.99 92.5531
10059.9792.7772710070.4694.0357610070.9594.1423610081.94100.858910092.92 106.688
10094.66106.9403 10103.9106.920210108.81 106.653
#Mann= 3 , 0 , 0
9893.402  0.0553       09893.402  0.0553       010108.81  0.0553       0
#XS Ineff= 2 , 0
       0                               0
Bank Sta=9893.402,10108.81
Exp/Cntr=0.3,0.1

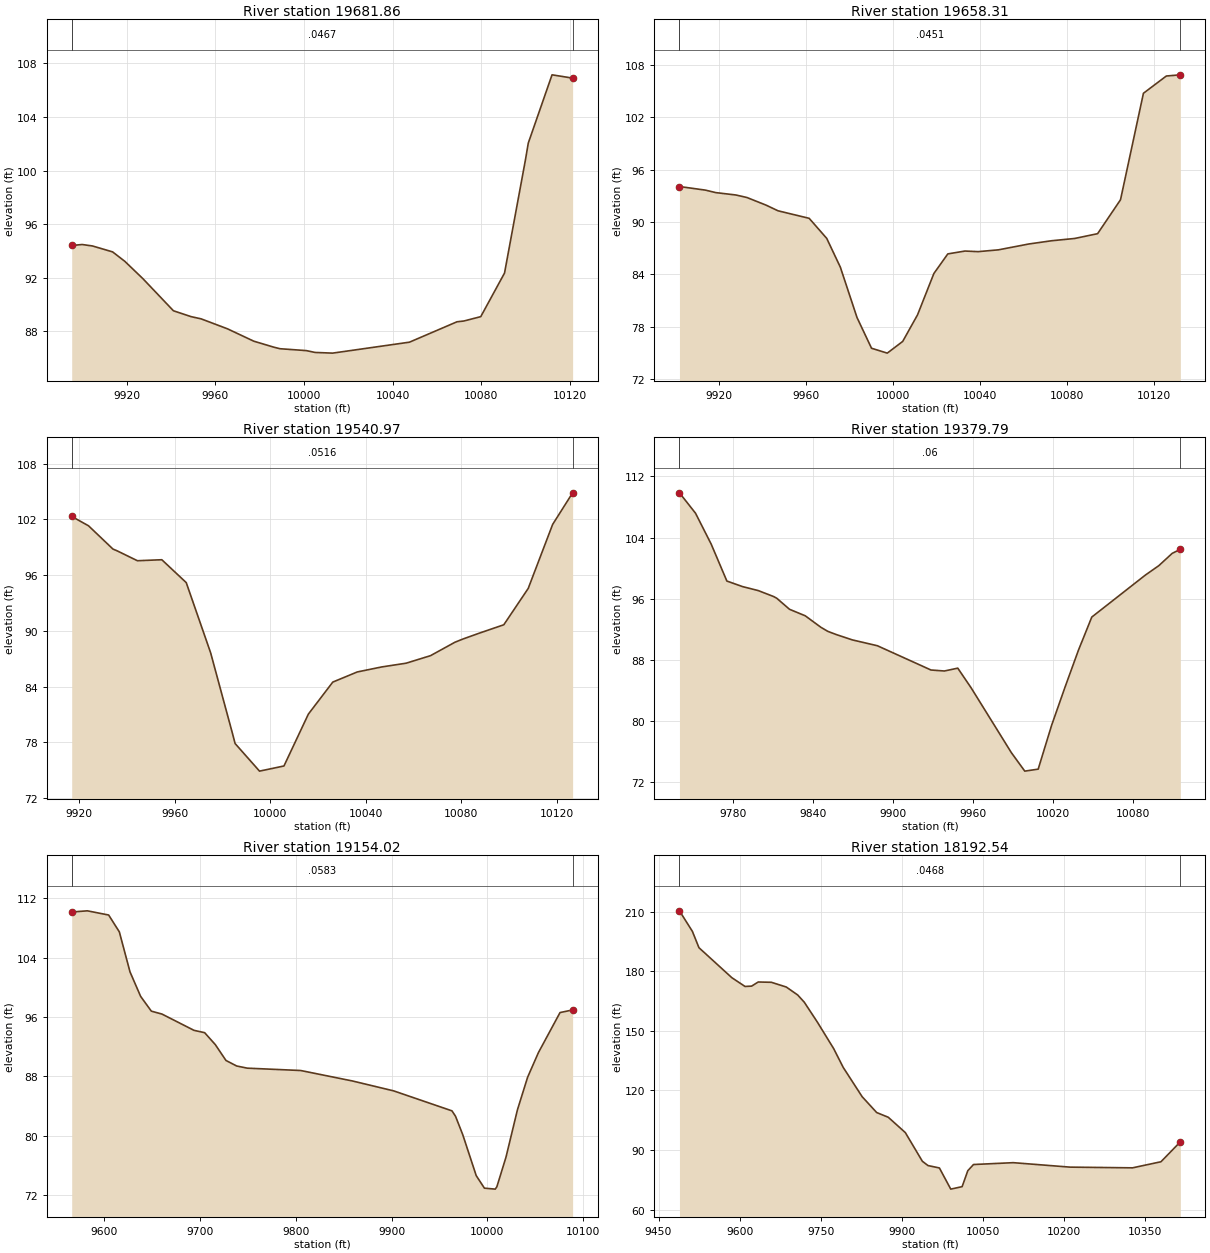
Type RM Length L Ch R = 1 ,19681.86,23.544900,23.544900,23.544900
XS GIS Cut Line= 5
395688.447738428849038.594633773395651.463062109849073.314868441
395585.051223649 849115.57476057395578.687163936  849122.2715057
395547.374621071849203.660433628
#Sta/Elev= 25
9895.25894.397389899.987 94.47049904.61794.362819913.70393.919219919.22793.21158
9927.41991.908739941.13589.519219949.12589.080649953.647 88.9145  9965.588.17157
9977.35387.248689986.37986.800699989.20686.6838610001.0686.5432710005.0186.40612
10012.91 86.355310047.5887.1739510069.0188.6975810072.0688.7535110079.7289.08107
10090.4492.3363510099.91100.830810101.15102.047710111.87 107.14910121.15106.9028
#Mann= 3 , 0 , 0
9895.258  0.0467       09895.258  0.0467       010121.15  0.0467       0
#XS Ineff= 2 , 0
       0                               0
Bank Sta=9895.258,10121.15
Exp/Cntr=0.3,0.1

Type RM Length L Ch R = 1 ,19658.31,117.342300,117.342300,117.342300
XS GIS Cut Line= 4
 395656.71019699849016.443716268 395625.85242883849048.026036515
395554.290618156849121.716311495395527.585084059849201.120364148
#Sta/Elev= 28
 9901.6194.053849913.57393.642049918.36693.356319927.55393.085629932.67692.79673
9941.53491.916379946.98991.273029961.34390.408199969.42688.107479975.69784.80628
9983.36579.034669990.05175.509279997.30474.94871 10004.476.2893210011.2479.33946
10018.7684.0792710025.1886.3271510033.1186.6560210039.1286.5864410048.48  86.794
 10062.587.4656610073.0587.83817 10083.688.0975110094.1588.64787 10104.7 92.5377
10115.25104.7491 10125.8106.728810132.26106.8647
#Mann= 3 , 0 , 0
 9901.61  0.0451       0 9901.61  0.0451       010132.26  0.0451       0
#XS Ineff= 2 , 0
       0                               0
Bank Sta=9901.61,10132.26
Exp/Cntr=0.3,0.1

Type RM Length L Ch R = 1 ,19540.97,161.179200,161.179200,161.179200
XS GIS Cut Line= 2
395461.050053011848998.107452234395504.517914383849203.181034776
#Sta/Elev= 26
9916.904102.32649923.949101.31619934.17198.809839935.953 98.61559944.39497.55563
9954.61697.661889964.83895.19781 9975.0687.624639984.17978.953419985.28277.86701
9995.50474.8951710005.7375.4493710015.9581.0391310026.1784.4865910032.4185.14978
10036.3985.5746410046.6286.1151710056.8486.5182410067.0687.3299110077.2888.77664
10080.6389.12267 10087.5 89.756810097.7390.6579710107.9594.5729610118.17 101.466
10126.53104.8681
#Mann= 3 , 0 , 0
9916.904  0.0516       09916.904  0.0516       010126.53  0.0516       0
#XS Ineff= 2 , 0
       0                               0
Bank Sta=9916.904,10126.53
Exp/Cntr=0.3,0.1

Type RM Length L Ch R = 1 ,19379.79,225.772100,225.772100,225.772100
XS GIS Cut Line= 3
395475.257805691848966.810149894395349.894306535849043.916389604
395329.814520623849271.096456902
#Sta/Elev= 30
9739.985109.85019752.028107.18099763.768103.13199775.50898.299349787.24897.57348
9798.98897.052339810.72896.256719812.88196.046469822.468 94.59869834.20893.75172
9845.94992.243979851.05691.718619857.68991.279999869.42990.598039888.25189.82965
9928.40786.652879938.446 86.52189948.48586.894819958.52484.308299988.64175.82766
 9998.6873.4127910008.7273.6723110018.76 79.4009 10028.884.3958310038.8489.22621
10048.8793.5825110089.0399.0838910099.07100.311910109.11101.923910115.23102.4539
#Mann= 3 , 0 , 0
9739.985    0.06       09739.985    0.06       010115.23    0.06       0
#XS Ineff= 2 , 0
       0                               0
Bank Sta=9739.985,10115.23
Exp/Cntr=0.3,0.1

Type RM Length L Ch R = 1 ,19154.02,961.478900,961.478900,961.478900
XS GIS Cut Line= 3
395509.655575912848914.242677749395301.981049756849016.261815668
395043.356187276849151.738817962
#Sta/Elev= 30
9565.828110.17159582.156110.33129604.439109.76579615.581107.49379626.722102.0985
9637.86498.782439649.00596.797319660.14796.401289693.57194.206439704.71293.88958
9715.85492.281969726.99590.141119738.137 89.39659749.27889.102929805.08988.78433
 9859.1487.373749902.24186.036319963.13483.341139966.893  82.5939974.42380.11001
9988.44374.605459997.00172.9115110008.2972.7811210009.9973.0905310019.5877.10847
10031.5483.4950610042.1687.8851610053.4591.2058510076.02 96.605410089.1796.95655
#Mann= 3 , 0 , 0
9565.828  0.0583       09565.828  0.0583       010089.17  0.0583       0
#XS Ineff= 2 , 0
       0                               0
Bank Sta=9565.828,10089.17
Exp/Cntr=0.3,0.1

Type RM Length L Ch R = 1 ,18192.54,706.652500,706.652500,706.652500
XS GIS Cut Line= 3
395427.586666739848195.352680647395217.848592704848497.668054593
395046.965336392849029.187870929
#Sta/Elev= 30
9488.696210.50319512.608200.16139524.779191.92139585.634176.80179609.976172.4013
9622.147172.56789634.318174.6461 9658.66174.49629686.208172.12169707.343168.1003
9719.514164.47129743.856154.38139773.924 141.0549791.467131.64149826.553116.8521
9853.395108.87619874.848106.4895 9906.36 98.77659937.87284.326899948.37782.15133
9969.38580.954959990.39370.28983 10011.471.5384110021.9179.5702110032.4182.68383
10105.9483.6183110210.9881.3713610326.5281.0145710379.0484.0736710414.9694.12567
#Mann= 3 , 0 , 0
9488.696  0.0468       09488.696  0.0468       010414.96  0.0468       0
#XS Ineff= 2 , 0
       0                               0
Bank Sta=9488.696,10414.96
Exp/Cntr=0.3,0.1

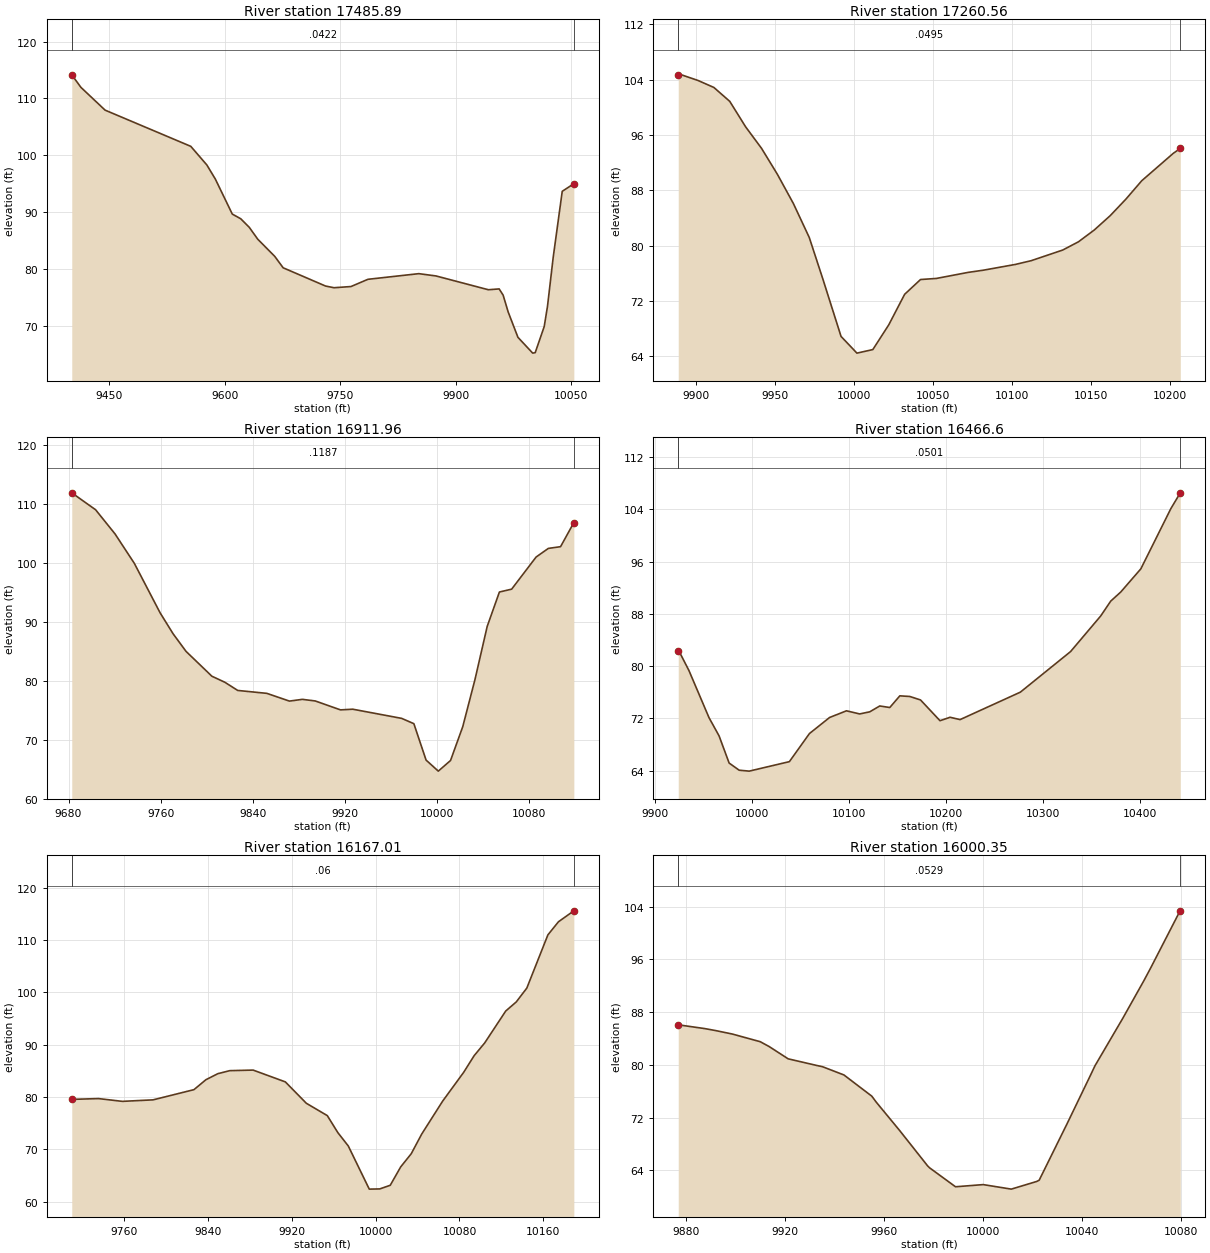
Type RM Length L Ch R = 1 ,17485.89,225.332700,225.332700,225.332700
XS GIS Cut Line= 3
394455.694893066848740.000927561394879.452830783848936.258493899
395037.872969689849032.829674514
#Sta/Elev= 30
9401.173114.15189413.068111.94879444.489107.9384 9555.84101.57249576.73498.29588
9587.75495.816789609.79589.656229620.81688.826879631.83687.327379642.85685.23829
9664.89782.227179675.91880.20439 9731.0276.99286 9742.0476.697269764.08176.90586
9786.12278.178689852.24479.171859874.66878.765469942.60376.343369956.64976.48643
9961.81575.393849968.36172.436079981.02767.9775810000.2465.19134 10003.565.27624
10015.2169.8673910019.4573.4130410026.9282.0854210038.63 93.658610053.7194.99274
#Mann= 3 , 0 , 0
9401.173  0.0422       09401.173  0.0422       010053.71  0.0422       0
#XS Ineff= 2 , 0
       0                               0
Bank Sta=9401.173,10053.71
Exp/Cntr=0.3,0.1

Type RM Length L Ch R = 1 ,17260.56,348.601900,348.601900,348.601900
XS GIS Cut Line= 3
 394702.58651136849105.529327229394862.091719683849087.083146672
395019.426789119849090.338355021
#Sta/Elev= 30
9888.819104.70249891.249104.67249901.315103.88779911.382102.87629921.449100.8637
9931.51597.172039941.58294.064699951.64990.294389961.71586.092169971.78281.17527
9980.474 75.10879991.915 66.856810001.9864.4364310012.0564.9501210022.1268.52309
10032.1872.9431910042.25 75.0845 10052.375.24317 10072.376.11353 10082.376.44624
10102.3177.2692810112.3177.8106410132.31 79.352410142.3280.5523110152.3282.26036
10162.3284.3146510172.3286.7209910182.3289.3743210202.3393.3477910206.7694.05422
#Mann= 3 , 0 , 0
9888.819  0.0495       09888.819  0.0495       010206.76  0.0495       0
#XS Ineff= 2 , 0
       0                               0
Bank Sta=9888.819,10206.76
Exp/Cntr=0.3,0.1

Type RM Length L Ch R = 1 ,16911.96,445.352300,445.352300,445.352300
XS GIS Cut Line= 3
394706.565099314849227.870907073 394906.21787709849329.867434848
395105.870654881849401.482018219
#Sta/Elev= 30
9682.794111.86419703.496108.99639720.446  104.889737.18499.896819759.64391.48394
9770.87287.952429782.10184.97247 9804.5680.759229815.78979.738459827.01978.34745
9852.33177.852429871.93676.541229883.16676.836679894.395 76.56349916.32275.05071
9926.94675.165649969.441 73.61239980.06572.714569990.68966.5367910001.31 64.6633
10011.9466.4634410022.5672.2011510033.1880.1954710043.8189.2103510054.4395.04343
10065.0695.52644 10086.3100.972610096.93102.437710107.55102.7298 10119.1106.8123
#Mann= 3 , 0 , 0
9682.794  0.1187       09682.794  0.1187       0 10119.1  0.1187       0
#XS Ineff= 2 , 0
       0                               0
Bank Sta=9682.794,10119.1
Exp/Cntr=0.3,0.1

Type RM Length L Ch R = 1 , 16466.6,299.588900,299.588900,299.588900
XS GIS Cut Line= 2
394534.315665321849419.578481469395034.294069839849555.137975727
#Sta/Elev= 30
9924.051 82.2736 9924.7682.312069935.12179.309799955.84372.090559966.20469.30928
9976.56565.153299986.92664.059789997.28763.9180510038.7365.3692410059.4169.66508
10080.1872.1253310097.63 73.151410111.2672.6719110121.6272.9943210131.9873.88988
10142.3473.65551 10152.775.4428110163.0675.3419810174.0574.8123810194.1571.63361
10204.5172.1612210214.8771.8049710277.0476.0056810328.8482.2155710359.9287.66337
10370.2889.9389610380.6591.3364210401.3794.8831810432.45104.133910442.08106.5172
#Mann= 3 , 0 , 0
9924.051  0.0501       09924.051  0.0501       010442.08  0.0501       0
#XS Ineff= 2 , 0
       0                               0
Bank Sta=9924.051,10442.08
Exp/Cntr=0.3,0.1

Type RM Length L Ch R = 1 ,16167.01,166.668200,166.668200,166.668200
XS GIS Cut Line= 5
394572.589345894849507.889371891394720.943894607849588.674127739
394756.133320374849596.482969274394943.844050166 849604.65916513
395029.591969875849614.136260324
#Sta/Elev= 30
9709.99879.552049735.51579.704129758.28879.173789787.597 79.46279826.60781.41324
9837.99483.31292 9849.3884.466499860.767 85.04499883.07685.153979913.80682.89977
9933.85178.80854 9953.8776.44645 9963.8873.206929973.88970.637569993.908 62.3897
10003.9262.4286510013.9363.1276310023.9466.6564710033.95 69.155810043.9672.92297
10063.9779.2297610083.9984.72705   1009487.9141710104.0290.3394810124.1496.45485
 10134.298.1938710144.26100.839910164.38111.017210174.44113.517110189.13115.6124
#Mann= 3 , 0 , 0
9709.998    0.06       09709.998    0.06       010189.13    0.06       0
#XS Ineff= 2 , 0
       0                               0
Bank Sta=9709.998,10189.13
Exp/Cntr=0.3,0.1

Type RM Length L Ch R = 1 ,16000.35,189.498500,189.498500,189.498500
XS GIS Cut Line= 2
394718.037775666849605.588576598394811.816835446 849785.59660154
#Sta/Elev= 29
9876.92986.078869887.541 85.51239891.99785.208389898.81684.677859910.09283.51351
9913.64182.790529921.36880.916779932.64379.935579935.284  79.7189943.91978.47068
9955.19575.247719956.92874.36846 9966.4770.025129977.74664.674469978.57264.37192
9989.02261.5046110000.2261.83214 10000.361.8282310011.5761.1464810021.8662.31131
10022.8562.5023710034.1271.06571 10043.578.35804 10045.479.8607510056.6887.09051
10065.1592.7577310067.9594.7265810079.23102.9544 10079.9 103.374
#Mann= 3 , 0 , 0
9876.929  0.0529       09876.929  0.0529       0 10079.9  0.0529       0
#XS Ineff= 2 , 0
       0                               0
Bank Sta=9876.929,10079.9
Exp/Cntr=0.3,0.1