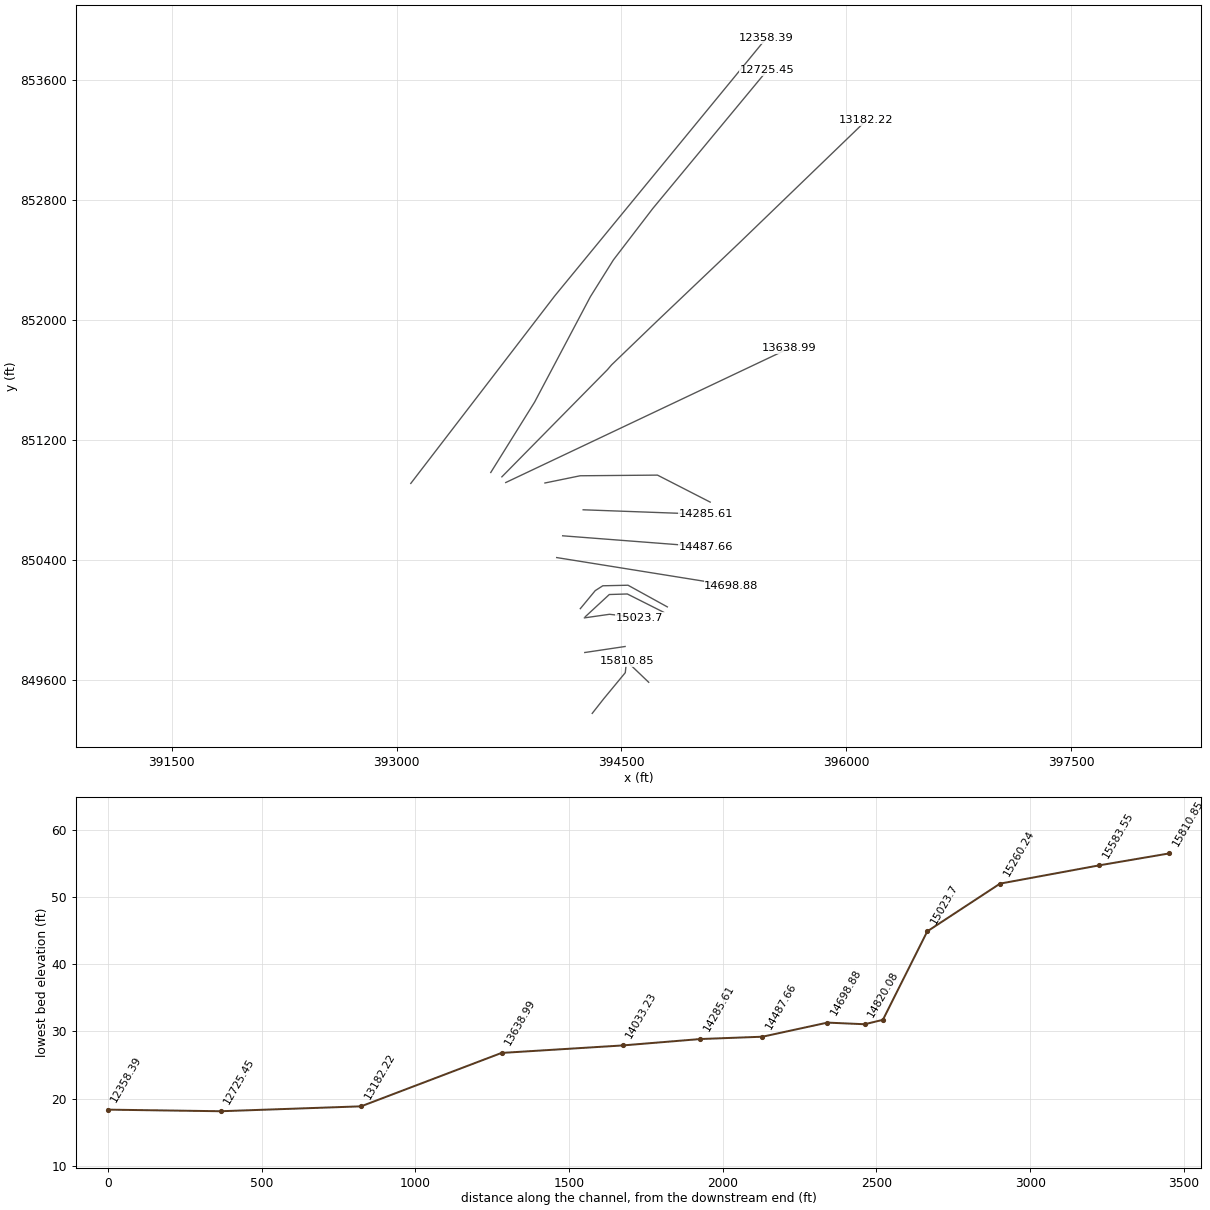
HEC-RAS study 6959_ras.prj: 6959

--- 6959_ras.g01 (geometry) --- (continued)

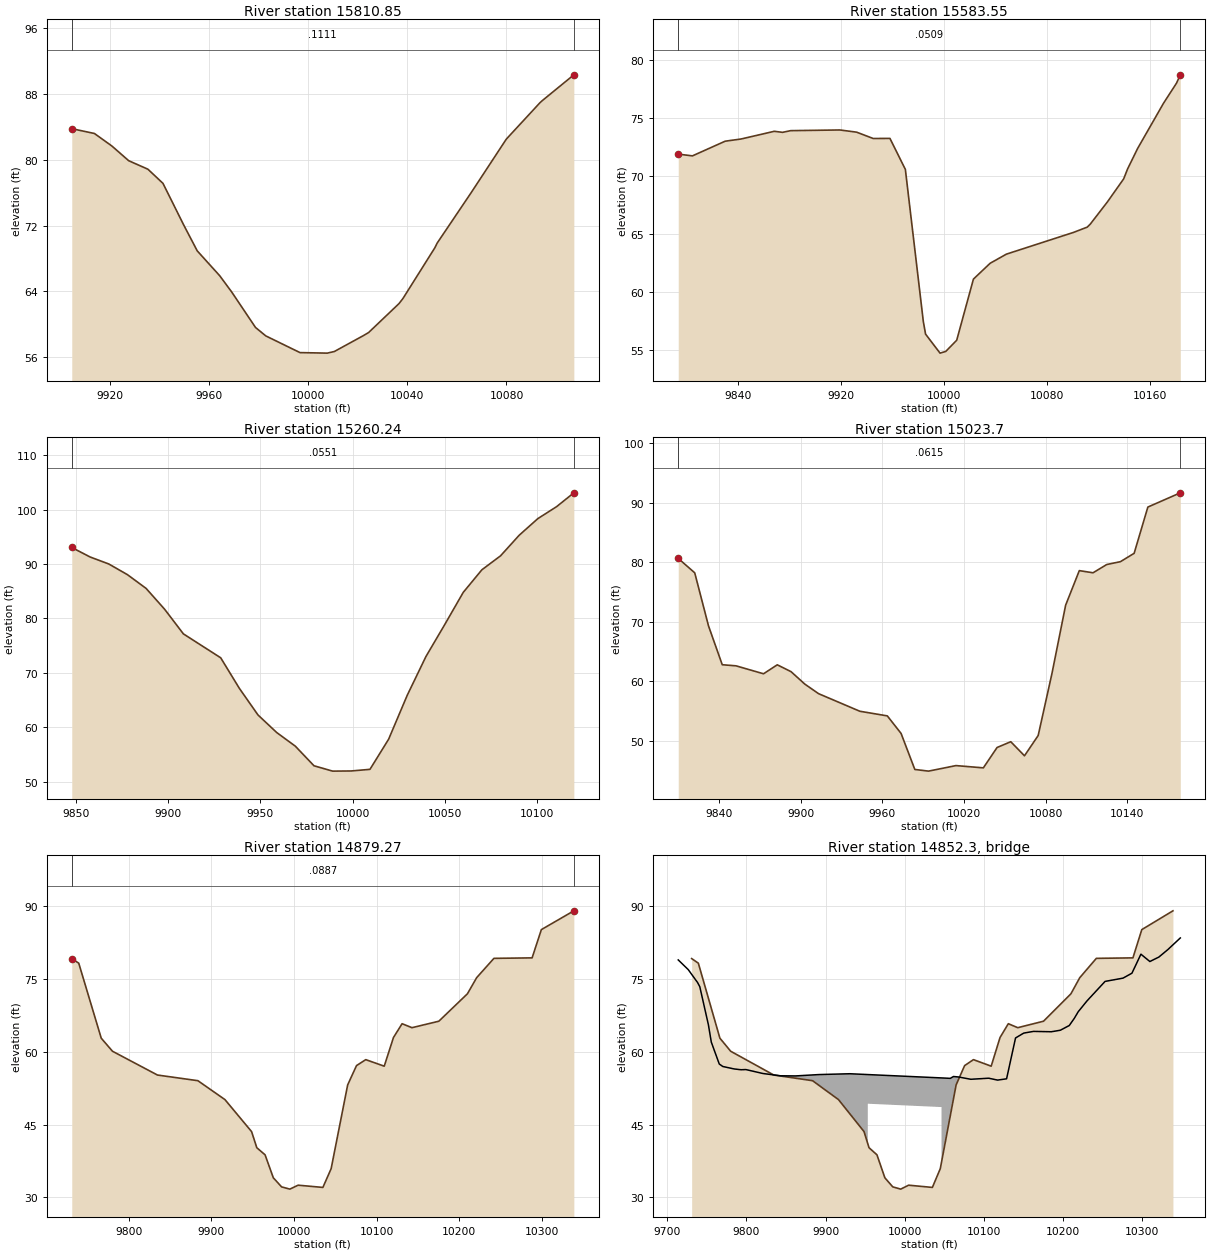
Type RM Length L Ch R = 1 ,15810.85,227.299400,227.299400,227.299400
XS GIS Cut Line= 2
394681.608502105849583.773684861394535.124127104849723.747643205
#Sta/Elev= 30
9904.568 83.81419906.34383.680249913.70983.209089920.81881.66915 9927.5479.89464
9935.29378.858389941.37277.135889949.76772.052389955.20368.914479964.24265.89731
9969.03463.940589978.71759.589019982.86658.560679993.19257.037239996.69756.52543
10007.6756.4625710010.5356.6592910022.1458.5762810024.3658.9696310036.6262.49289
10038.1963.1029310051.0969.2911110052.0269.8579110065.57 75.925110065.8576.05141
10079.6982.4130710080.0482.5573610093.5286.9576910094.5287.2300210107.1890.35148
#Mann= 3 , 0 , 0
9904.568  0.1111       09904.568  0.1111       010107.18  0.1111       0
#XS Ineff= 2 , 0
       0                               0
Bank Sta=9904.568,10107.18
Exp/Cntr=0.3,0.1

Type RM Length L Ch R = 1 ,15583.55,323.312000,323.312000,323.312000
XS GIS Cut Line= 4
394304.879179178849376.331621946394380.804229767849472.861162675
394525.358502178849647.792782116394529.698779851849687.940351532
#Sta/Elev= 30
9793.74271.85342 9804.7771.701449830.215 72.96769842.46373.153819868.38373.82058
9874.81473.730759881.10673.876659919.32773.93542  9932.3 73.74779945.27273.19915
9958.24573.207939970.235 70.5304 9984.1957.412559985.93456.328939997.162 54.6918
10001.6354.8398210010.1355.8043210023.1161.0750210036.0862.4387610048.7363.22786
10100.9465.1042710111.52 65.556410113.9165.8174610127.2267.7327110139.8669.72136
10142.9270.5807510150.7372.3485310170.85 76.246310180.9177.9728910183.8678.69077
#Mann= 3 , 0 , 0
9793.742  0.0509       09793.742  0.0509       010183.86  0.0509       0
#XS Ineff= 2 , 0
       0                               0
Bank Sta=9793.742,10183.86
Exp/Cntr=0.3,0.1

Type RM Length L Ch R = 1 ,15260.24,236.540800,236.540800,236.540800
XS GIS Cut Line= 2
394255.176210419849782.341393215394524.273432658849822.488962643
#Sta/Elev= 27
9847.86493.041569857.79691.300459867.90790.016299878.01888.055749888.129 85.5322
9898.239 81.6769 9908.3577.176769928.57172.783059938.68267.170559948.79362.27542
9958.903   59.069969.01456.548219979.12552.947959989.23551.965219999.34651.99516
10009.4652.2931510019.5757.8253310029.68 65.914510039.7973.01402 10049.978.83885
10060.0184.8003210070.1288.9505110080.2391.5139710090.3495.2983110100.4598.35173
10110.56100.534910119.94103.0832
#Mann= 3 , 0 , 0
9847.864  0.0551       09847.864  0.0551       010119.94  0.0551       0
#XS Ineff= 2 , 0
       0                               0
Bank Sta=9847.864,10119.94
Exp/Cntr=0.3,0.1

Type RM Length L Ch R = 1 , 15023.7,144.424400,144.424400,144.424400
XS GIS Cut Line= 3
394253.006071538850013.461184844   394420.106766850037.332712634
394618.674474328850014.546254322
#Sta/Elev= 30
9810.221 80.62849822.337 78.20299832.43969.29335 9842.5462.753619852.64262.56928
9872.84561.234149882.94662.740589893.048 61.59179903.14959.503039913.25157.89165
9943.55554.936429963.75854.15362 9973.86 51.20499983.94445.14902 9994.0144.86967
10014.1445.7994710034.2745.4193810044.3448.84119 10054.449.8114510064.4747.44731
10074.5350.85717 10084.661.2346510094.67 72.752410104.7378.57379 10114.878.21051
10124.8679.5978810134.9380.0791110144.9981.4837110155.0689.2572310178.8991.65148
#Mann= 3 , 0 , 0
9810.221  0.0615       09810.221  0.0615       010178.89  0.0615       0
#XS Ineff= 2 , 0
       0                               0
Bank Sta=9810.221,10178.89
Exp/Cntr=0.3,0.1

Type RM Length L Ch R = 1 ,14879.27,59.185900,59.185900,59.185900
XS GIS Cut Line= 4
394258.796765804850021.283158451394418.692599148850169.199825138
394539.005099148850172.845658451394780.150932491 850051.49149178
#Sta/Elev= 30
 9730.85 79.14839739.30178.195019766.54662.764069780.16960.079279834.659 55.1814
9883.58354.019629916.39550.126859948.67143.539329954.981 40.22599964.98638.76776
9974.99134.036939984.99532.16925    999531.70593   10005 32.515710035.0232.05699
10045.0235.9113110065.0353.1465610075.7557.1197310086.9458.3509410109.3357.00531
10120.5362.9096210130.98 65.743710142.9264.9257810175.4766.2556210210.09 71.8971
10221.28 75.217710242.2179.1918910288.4579.2910810299.6585.10502   1033988.97106
#Mann= 3 , 0 , 0
 9730.85  0.0887       0 9730.85  0.0887       0   10339  0.0887       0
#XS Ineff= 2 , 0
       09940.343        10070.51       0
Bank Sta=9730.85,10339
Exp/Cntr=0.3,0.1

Type RM Length L Ch R = 3 , 14852.3,,,
BEGIN DESCRIPTION:
END DESCRIPTION:
Bridge Culvert--1,0,-1,-1, 0
Deck Dist Width WeirC Skew NumUp NumDn MinLoCord MaxHiCord MaxSubmerge Is_Ogee
15.813450,27.559000,2.6,0, 45, 45, , , 0.95, 0, 0,0,,
 9713.89 9726.56 9738.22 9741.11 9751.98 9755.67 9765.74 9770.22 9784.78 9793.27
 9799.33 9820.79 9842.99 9862.08 9891.73 9930.84 9953.41 9953.4110046.5910046.59
10057.6410061.6810067.7910083.5310106.1610117.4810128.7910140.1110150.2410151.42
10162.7410185.3710196.6810208.0010214.3610219.3110230.6310253.2610275.8910287.20
10298.5210309.8310321.2210332.4610348.31
   78.87   76.87   74.24   73.37   65.54   61.96   57.45   56.94   56.43   56.27
   56.31   55.50   55.03   55.00   55.28   55.45   55.28   55.28   54.59   54.59
   54.50   54.88   54.79   54.31   54.53   54.14   54.41   62.81   63.79   63.84
   64.16   64.09   64.40   65.37   66.85   68.21   70.48   74.45   75.12   76.14
   80.05   78.54   79.46   80.98   83.39
 -921.13 -923.13 -925.76 -926.63 -934.46 -938.04 -942.55 -943.06 -943.57 -943.73
 -943.69 -944.50 -944.97 -945.00 -944.72 -944.55 -944.72   49.28   48.59 -945.41
 -945.50 -945.12 -945.21 -945.69 -945.47 -945.86 -945.59 -937.19 -936.21 -936.16
 -935.84 -935.91 -935.60 -934.63 -933.15 -931.79 -929.52 -925.55 -924.88 -923.86
 -919.95 -921.46 -920.54 -919.02 -916.61
 9713.89 9726.56 9738.22 9741.11 9751.98 9755.67 9765.74 9770.22 9784.78 9793.27
 9799.33 9820.79 9842.99 9862.08 9891.73 9930.84 9953.41 9953.4110046.5910046.59
10057.6410061.6810067.7910083.5310106.1610117.4810128.7910140.1110150.2410151.42
10162.7410185.3710196.6810208.0010214.3610219.3110230.6310253.2610275.8910287.20
10298.5210309.8310321.2210332.4610348.31
   78.87   76.87   74.24   73.37   65.54   61.96   57.45   56.94   56.43   56.27
   56.31   55.50   55.03   55.00   55.28   55.45   55.28   55.28   54.59   54.59
   54.50   54.88   54.79   54.31   54.53   54.14   54.41   62.81   63.79   63.84
   64.16   64.09   64.40   65.37   66.85   68.21   70.48   74.45   75.12   76.14
   80.05   78.54   79.46   80.98   83.39
 -921.13 -923.13 -925.76 -926.63 -934.46 -938.04 -942.55 -943.06 -943.57 -943.73
 -943.69 -944.50 -944.97 -945.00 -944.72 -944.55 -944.72   49.28   48.59 -945.41
 -945.50 -945.12 -945.21 -945.69 -945.47 -945.86 -945.59 -937.19 -936.21 -936.16
 -935.84 -935.91 -935.60 -934.63 -933.15 -931.79 -929.52 -925.55 -924.88 -923.86
 -919.95 -921.46 -920.54 -919.02 -916.61
BR Coef=-1 , 0 , 0 ,, 0 ,,,0.8,0,1,0,
WSPro=,,,, 1 ,,,, 0 ,,,, 0 ,,,,-1 ,-1 ,-1 , 0 , 0 , 0 , 0 , 0
BC Design=,, 0 ,, 0 ,,,,,,

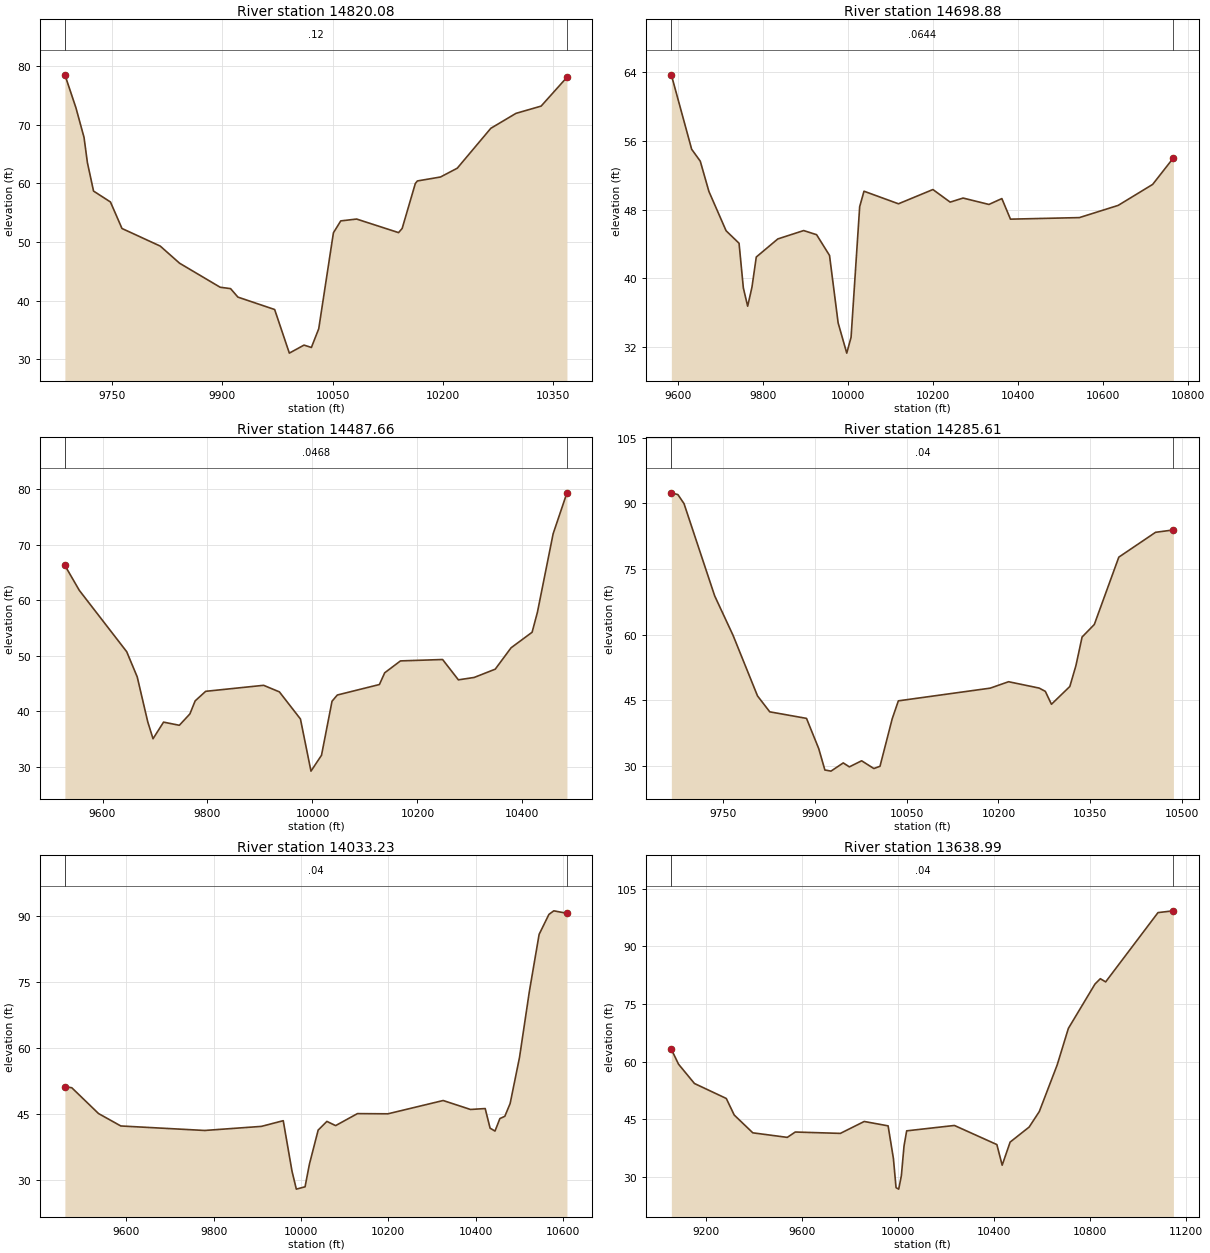
Type RM Length L Ch R = 1 ,14820.08,121.201900,121.201900,121.201900
XS GIS Cut Line= 5
394225.463432491 850074.92899178394324.942599148850195.241491795
394375.463432491850227.533158451394543.692599148 850231.17899178
394805.799445838850086.661275342
#Sta/Elev= 30
9685.39878.524539700.36472.929279711.44267.861239716.05763.542399724.41758.69382
9747.44356.832469763.13652.310259815.24749.308229841.57946.386079896.76742.29149
9911.00942.049069921.01240.603249971.02338.487359991.02831.0481510011.03 32.4191
10021.0432.0116810031.0435.1991110051.0451.5760610061.0453.6063810082.65 53.9208
10139.7551.6051410144.6752.3230910162.59  59.98810165.3860.4197210196.8461.09385
10219.68 62.593910265.3669.4000110299.6271.9507310333.8873.1891510369.0578.10645
#Mann= 3 , 0 , 0
9685.398    0.12       09685.398    0.12       010369.05    0.12       0
#XS Ineff= 2 , 0
       09914.094        10064.96       0
Bank Sta=9685.398,10369.05
Exp/Cntr=0.3,0.1

Type RM Length L Ch R = 1 ,14698.88,211.218600,211.218600,211.218600
XS GIS Cut Line= 2
394067.851233013850415.702092894395233.203721443850228.642930114
#Sta/Elev= 30
9584.94763.707549632.69955.037939652.955  53.6499673.21150.129199713.72345.53826
9744.10744.089599754.23538.880049764.36336.755089774.49138.981939784.61942.48592
9835.25944.592039896.02745.566949926.41145.085989956.79542.669339977.051 34.8105
9997.30731.2907810007.4433.1336810027.69 48.349610037.8250.1505610118.8448.68554
10199.8750.3460410240.3848.8801910270.7649.3542210331.5348.6096410361.9249.29263
10382.1746.8961210544.2247.0773510635.37  48.499 10716.4 50.941410765.2254.03067
#Mann= 3 , 0 , 0
9584.947  0.0644       09584.947  0.0644       010765.22  0.0644       0
#XS Ineff= 2 , 0
       09785.666        10048.64       0
Bank Sta=9584.947,10765.22
Exp/Cntr=0.3,0.1

Type RM Length L Ch R = 1 ,14487.66,202.053900,202.053900,202.053900
XS GIS Cut Line= 2
 394107.59608821850560.935494979395061.203322278850487.379809677
#Sta/Elev= 30
9528.34866.263189555.83461.766489646.10150.714919666.16146.16755 9686.2238.06525
 9696.2535.030769716.30938.023979746.39837.454259766.45839.500569776.48741.84993
9796.54743.575019906.87344.657589936.96343.477869977.08138.588029997.14129.19291
 10017.232.0521310037.2641.7926510047.2942.9066210127.5344.8006810137.5646.91043
10167.6549.0559310247.8849.3073210277.9745.6430110308.0646.0743310348.1847.56714
10378.2751.4123310418.39 54.221110428.4257.7818810458.5171.9849410484.7979.34611
#Mann= 3 , 0 , 0
9528.348  0.0468       09528.348  0.0468       010484.79  0.0468       0
#XS Ineff= 2 , 0
       09681.868        10187.98       0
Bank Sta=9528.348,10484.79
Exp/Cntr=0.3,0.1

Type RM Length L Ch R = 1 ,14285.61,252.383200,252.383200,252.383200
XS GIS Cut Line= 2
394244.290335703850734.438392354 395064.15623383850704.439536984
#Sta/Elev= 30
  9665.592.417879676.21792.008939686.22389.949449736.25768.895489766.27759.88594
9806.30446.028439826.31742.391949886.35740.895719906.371 33.97689916.37729.10807
9926.38428.847729946.39730.722359956.40429.821769976.41831.210499996.43129.44099
10006.4429.9514610026.45 40.824310036.4644.9010610186.5647.8032410216.5849.27131
10266.6147.8146810276.6247.0690910286.6244.1199410316.6548.1817410326.6552.96641
10336.6659.4785410356.6762.34579 10396.777.7267910456.7483.3998310485.9183.94093
#Mann= 3 , 0 , 0
  9665.5    0.04       0  9665.5    0.04       010485.91    0.04       0
#XS Ineff= 2 , 0
       09845.962        10217.46       0
Bank Sta=9665.5,10485.91
Exp/Cntr=0.3,0.1

Type RM Length L Ch R = 1 ,14033.23,394.241500,394.241500,394.241500
XS GIS Cut Line= 4
393989.435728873850913.210780318394224.505144031850961.388634499
394740.209040289850965.741344199395091.771540286 850785.61981644
#Sta/Elev= 30
9458.84351.242499474.73150.966819535.97845.097529587.01742.271779779.296 41.2472
9909.30142.177989959.30343.473029979.30332.010859989.30427.89555 10009.328.42528
 10019.333.5859510039.3141.3279110059.3143.3153210079.3142.3531810129.3145.08329
10199.3145.04138 10325.848.0653610388.4546.0289710422.1546.2360810433.3941.76904
10444.6341.1141810455.8643.96313 10467.144.4658610479.3147.3814910500.8157.87772
10523.2872.8358210545.7585.8850810568.2290.4378210579.4691.2444510609.5490.67123
#Mann= 3 , 0 , 0
9458.843    0.04       09458.843    0.04       010609.54    0.04       0
#XS Ineff= 2 , 0
       09834.674        10290.49       0
Bank Sta=9458.843,10609.54
Exp/Cntr=0.3,0.1

Type RM Length L Ch R = 1 ,13638.99,456.767300,456.767300,456.767300
XS GIS Cut Line= 2
393727.924750526850916.203000394395620.472610851851812.513094868
#Sta/Elev= 30
9054.59863.224099084.55659.332119150.94554.299819283.72250.400039316.91646.08174
 9394.3741.447819538.21240.260779571.40741.656359759.50841.301449859.09144.40363
9958.67443.263449980.80434.760649991.86927.1535710002.9326.77981   1001430.28281
10025.0637.9996210036.1341.9632110235.2943.3654110412.3338.3863710434.4633.01543
10467.6539.0349710547.0342.9542110589.3747.0002610663.8559.1320810710.5768.65537
10821.7380.2222310843.8681.6017510865.9980.7656111084.3898.8212411148.66 99.2834
#Mann= 3 , 0 , 0
9054.598    0.04       09054.598    0.04       011148.66    0.04       0
#XS Ineff= 2 , 0
       0 9613.64        10063.01       0
Bank Sta=9054.598,11148.66
Exp/Cntr=0.3,0.1

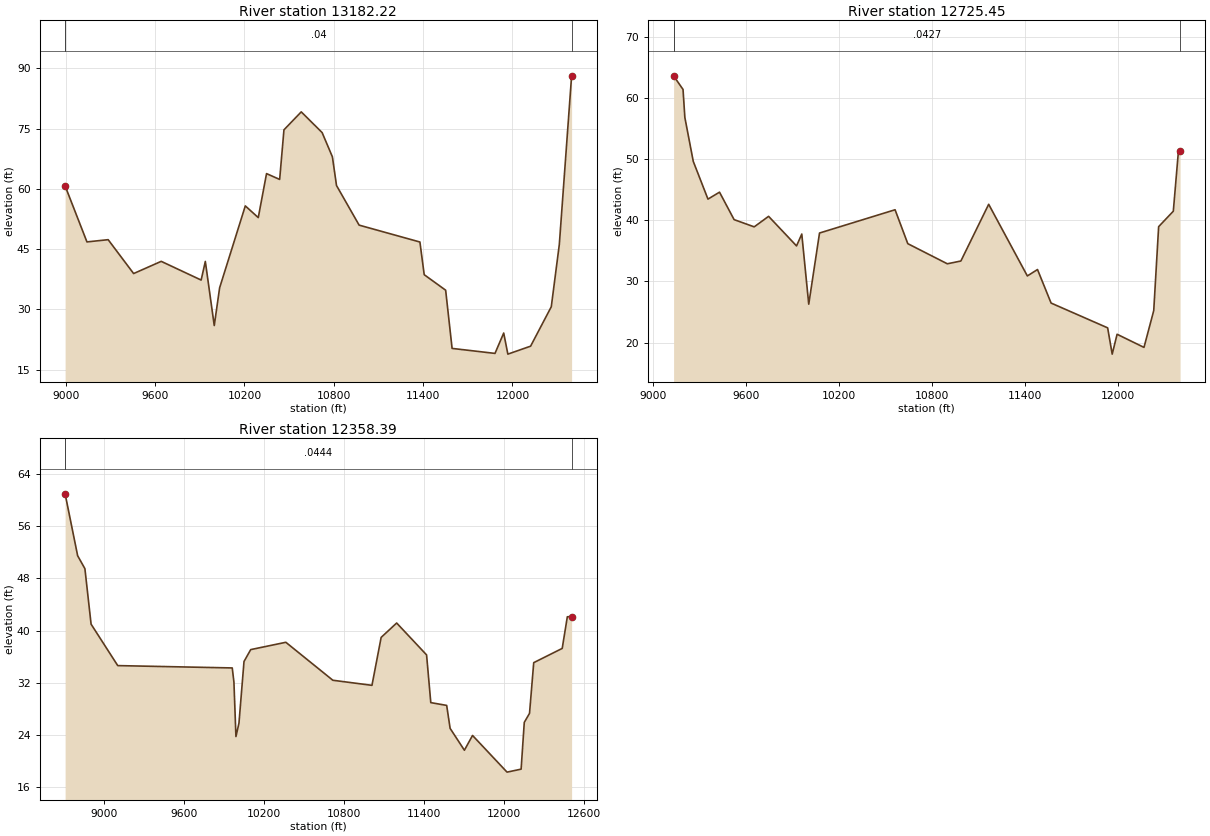
Type RM Length L Ch R = 1 ,13182.22,456.766100,456.766100,456.766100
XS GIS Cut Line= 6
393702.101878422850954.289793009394406.141191095851668.879320425
394433.663743278851700.815595795394736.723841702 851992.55814994
395284.933818216852513.904915244396133.161082735853332.217246818
#Sta/Elev= 30
 8995.8560.744999142.46446.790149284.94947.344999455.93138.906549641.16241.94754
9909.32537.288059937.40241.927729997.37425.95774 10033.4 35.353610205.83 55.7624
10292.89 52.846110348.4163.8032810436.53 62.353610465.3974.7073310581.4879.18503
10721.6774.0275410790.6767.9890610818.2760.8421710970.0750.9727711378.3946.76283
 11407.238.6248611551.2334.7585711594.43 20.260811882.4919.0166211941.0124.09187
11968.9118.8364112121.6520.81725 12260.630.6415612314.5846.1882212396.9988.16333
#Mann= 3 , 0 , 0
 8995.85    0.04       0 8995.85    0.04       012396.99    0.04       0
#XS Ineff= 2 , 0
       09606.752        10238.94       0
Bank Sta=8995.85,12396.99
Exp/Cntr=0.3,0.1

Type RM Length L Ch R = 1 ,12725.45,367.066300,367.066300,367.066300
XS GIS Cut Line= 6
393628.052057777850983.265654579393920.626854191851453.156375633
394292.292895464852155.441822664394445.799711684852400.791543934
394708.811438774852744.233539783395472.706778244853666.464497915
#Sta/Elev= 30
9130.74963.67823 9191.6461.44317 9203.4156.855119257.69349.667939352.50143.49011
9427.03744.626929521.19640.131259650.90238.946389743.751 40.66959924.10135.82507
9957.84837.7709510002.8126.2867710072.3937.9362110559.8741.7475110641.8836.19469
10896.97 32.899410984.5133.3549811163.8942.6410111413.3130.9095811478.9531.95714
11566.5926.4677911931.5322.4088411960.9118.1068211992.4621.3597412165.96 19.2115
12228.9425.23432 12260.638.9797112355.24 41.511212386.7850.9157612398.9451.34591
#Mann= 3 , 0 , 0
9130.749  0.0427       09130.749  0.0427       012398.94  0.0427       0
#XS Ineff= 2 , 0
       09759.508        10442.82       0
Bank Sta=9130.749,12398.94
Exp/Cntr=0.3,0.1

Type RM Length L Ch R = 1 ,12358.39,644.874000,644.874000,644.874000
XS GIS Cut Line= 3
393094.583329197850910.378373104394054.029508205852160.229156078
395465.340676537853879.460382191
#Sta/Elev= 30
 8708.5560.942728802.62351.465538857.03749.486238903.47740.991549103.37434.64814
9962.438 34.29089975.04532.126699990.18723.7875810012.8625.8343210050.6935.27741
10101.1137.0983310364.5338.2173610717.3232.4047411010.7131.6283711079.58 38.9645
11196.0241.1673311420.4936.2845211452.01 28.983111571.2128.5547711597.09  25.041
11704.1821.6957911765.2823.9575312024.04 18.343312129.7218.7986612153.4225.95701
12192.7627.3388312224.2835.0991712438.05 37.280512476.4542.1231812508.5142.14704
#Mann= 3 , 0 , 0
 8708.55  0.0444       0 8708.55  0.0444       012508.51  0.0444       0
#XS Ineff= 2 , 0
       09465.152        10354.52       0
Bank Sta=8708.55,12508.51
Exp/Cntr=0.3,0.1