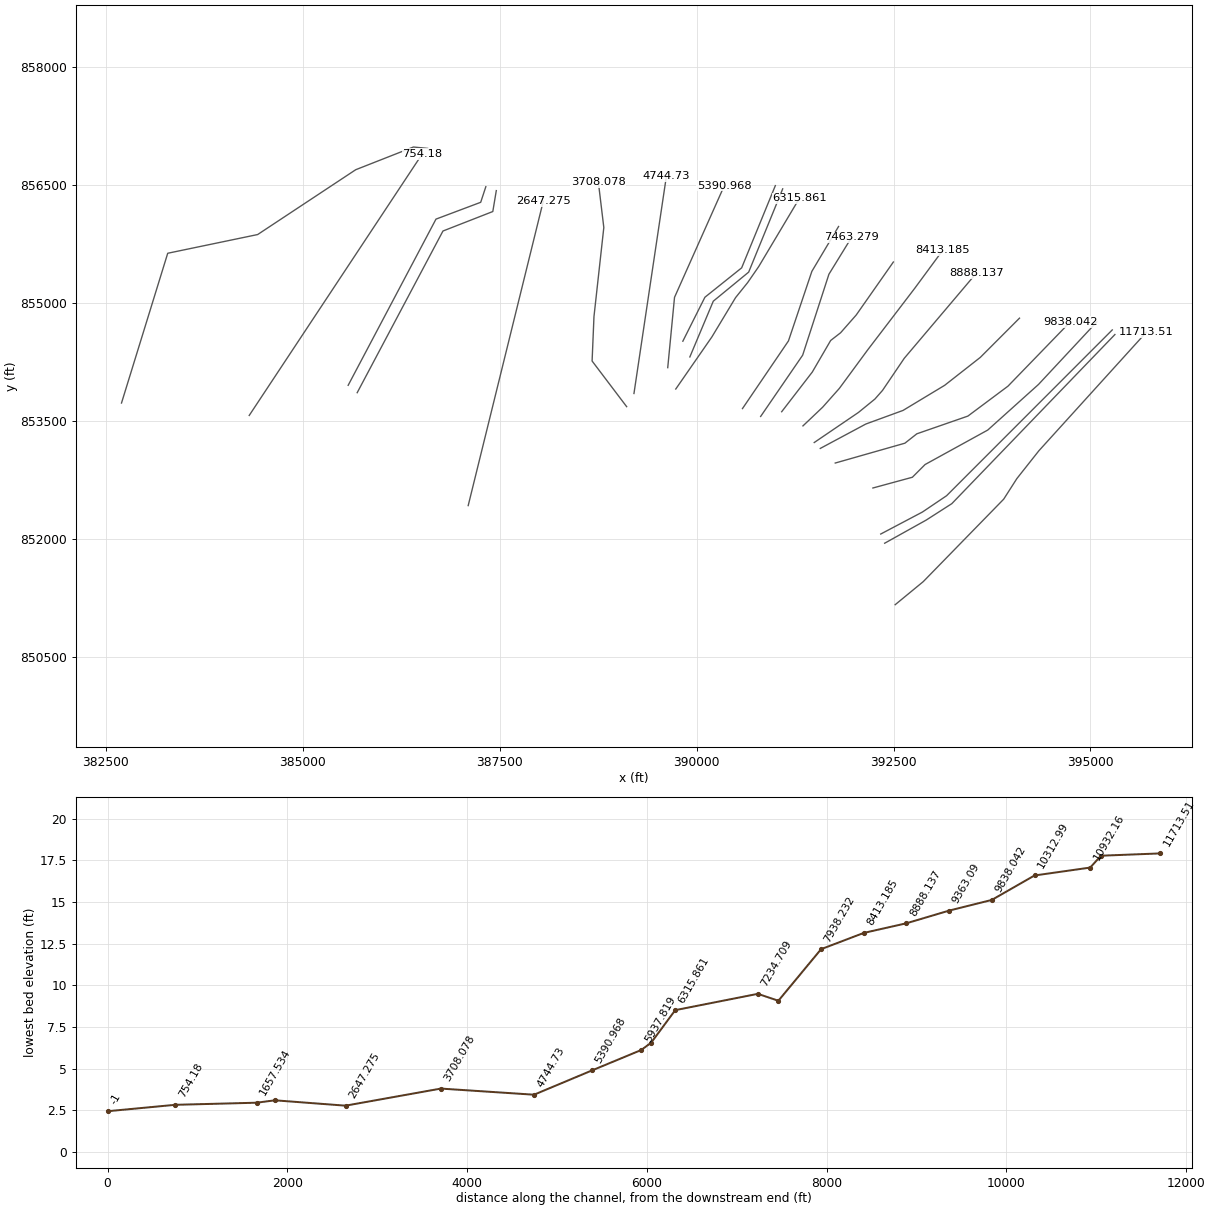
HEC-RAS study 6959_ras.prj: 6959

--- 6959_ras.g01 (geometry) --- (continued)

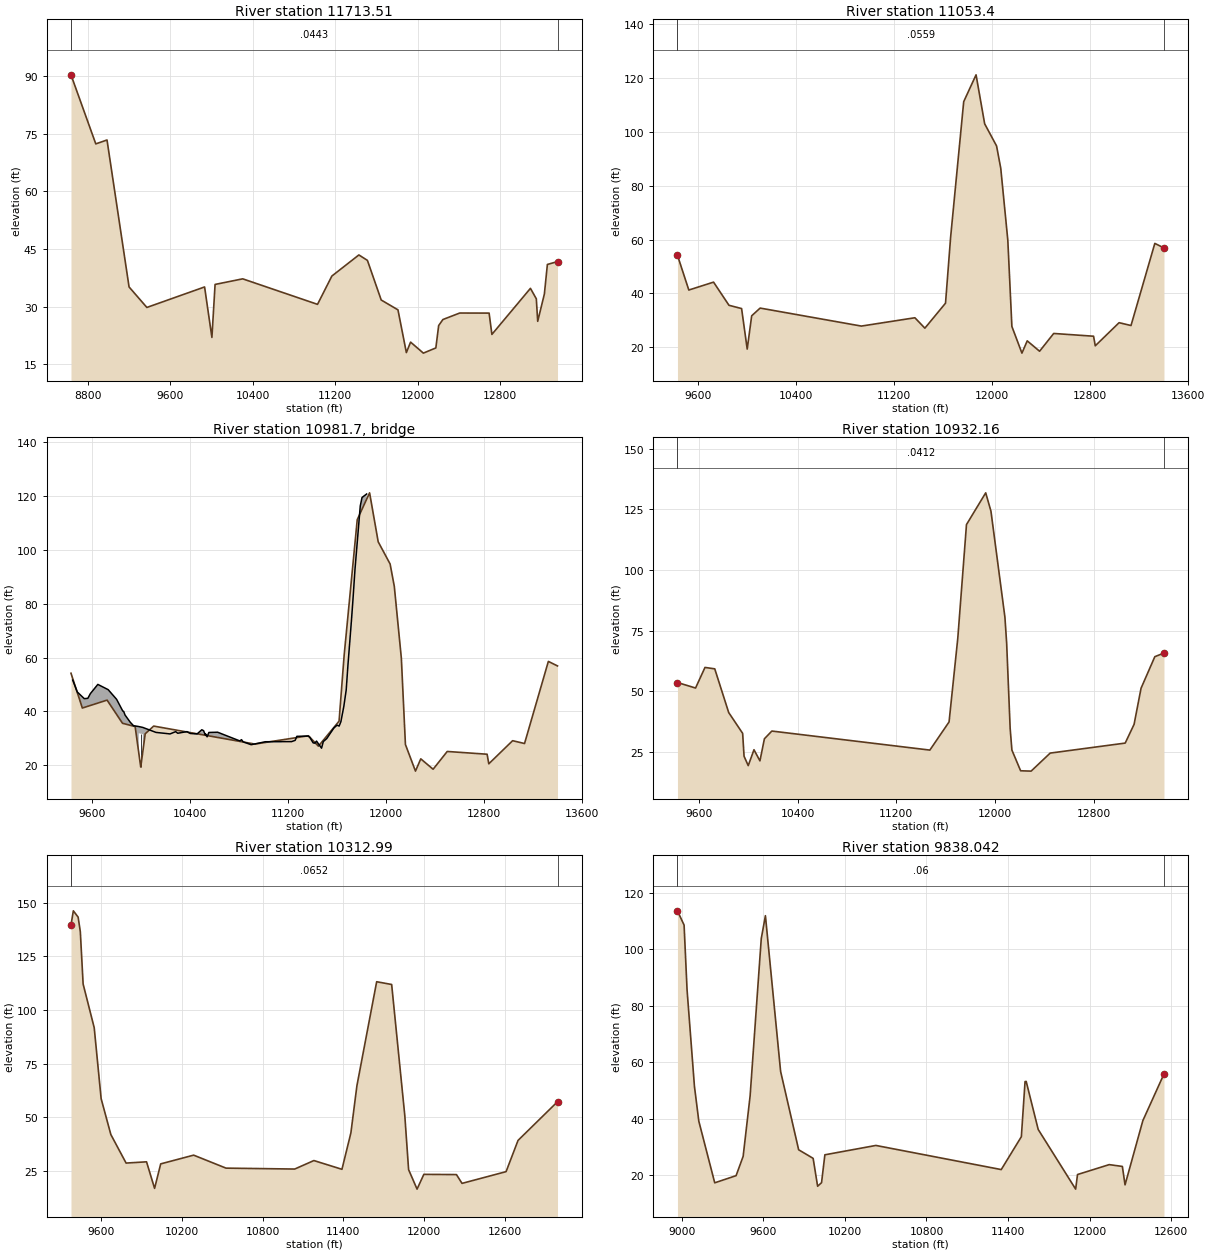
Type RM Length L Ch R = 1 ,11713.51,660.107300,660.107300,660.107300
XS GIS Cut Line= 6
392521.103184248851169.604842918392877.557287076851462.595971822
393898.224409641852508.972325852394065.604510196852770.355890596
394345.149431889853123.711553035395709.348587475854628.627114217
#Sta/Elev= 30
8638.72690.279158879.035 72.32498987.967 73.33469201.73935.127949374.34129.79598
9933.87235.1256210004.8222.0066510035.6135.7815510303.4437.2344511028.7530.60022
11167.8337.9616511429.5443.4469211512.3742.0372711646.1531.7323311808.58   29.17
11890.0518.0584711930.8820.7844112054.8117.9205212175.8619.2749412203.08 25.0856
12243.91 26.652312407.2328.3444112692.1228.3276912719.1722.7896413092.8534.76436
 13149.832.0402313163.2126.1812913227.9333.2956813257.07 40.973113355.2441.72249
#Mann= 3 , 0 , 0
8638.726  0.0443       08638.726  0.0443       013355.24  0.0443       0
#XS Ineff= 2 , 0
       09225.776        10326.01       0
Bank Sta=8638.726,13355.24
Exp/Cntr=0.3,0.1

Type RM Length L Ch R = 1 , 11053.4,121.248200,121.248200,121.248200
XS GIS Cut Line= 4
 392387.60500139 851949.85571976392914.688334703 852243.60571976
393239.688334733852451.939053118395309.924220741854598.756518215
#Sta/Elev= 30
9430.17954.159559522.91341.224019724.84844.163849850.77735.556639953.81134.34371
9999.60319.2971510036.17 31.655510105.2334.51885 10931.527.8309211368.5530.92424
11450.1227.0564111618.61 36.341211660.2960.8821411767.05111.212211867.89121.1923
11938.13103.003412035.3894.7567712069.5886.45662 12127.259.7189812160.4127.68874
12242.4517.7824812285.6722.3458712386.5118.4851712501.7625.0891212827.2324.06488
12841.1220.5037213035.6229.0926913132.8628.0389313327.3558.5507113402.0356.87261
#Mann= 3 , 0 , 0
9430.179  0.0559       09430.179  0.0559       013402.03  0.0559       0
#XS Ineff= 2 , 0
       0                 10532.9       0
Bank Sta=9430.179,13402.03
Exp/Cntr=0.3,0.1

Type RM Length L Ch R = 3 , 10981.7,,,
BEGIN DESCRIPTION:
END DESCRIPTION:
Bridge Culvert--1,0,-1,-1, 0
Deck Dist Width WeirC Skew NumUp NumDn MinLoCord MaxHiCord MaxSubmerge Is_Ogee
43.891850,33.464500,2.6,0, 60, 60, , , 0.95, 0, 0,0,,
 9444.25 9481.40 9538.79 9567.76 9588.14 9649.29 9733.88 9802.74 9853.10 9860.12
 9871.60 9914.24 9940.46 9983.27 9983.2710016.7310016.7310124.0810238.8410284.75
10301.4910376.5610403.3910460.1710498.2710512.6410527.0210529.7910541.3910555.76
10627.2410808.2310822.1610836.0810900.7111017.0711231.2811260.0211274.3911365.13
11379.0511406.9011420.8211434.7411475.6111489.9811518.2711576.2211601.8111619.34
11633.7111657.5011676.8311691.2011719.9511734.3211748.6911791.8111806.1811843.79
   51.59   47.20   44.71   44.84   46.57   50.01   48.05   44.45   40.10   39.99
   38.62   35.93   34.67   34.35   34.35   34.02   34.02   32.17   31.61   32.45
   31.86   32.46   31.78   31.62   33.16   32.81   31.17   31.56   30.54   32.15
   32.24   29.01   29.47   28.66   27.60   28.70   28.75   29.22   30.71   30.81
   30.39   28.29   28.17   28.94   26.31   28.76   29.89   33.81   34.86   34.53
   36.19   41.83   47.88   57.19   73.88   82.92   92.78  116.35  119.46  120.76
 -948.41 -952.80 -955.29 -955.16 -953.43 -949.99 -951.95 -955.55 -959.90 -960.01
 -961.38 -964.07 -965.33 -965.65   31.85   31.52 -965.98 -967.83 -968.39 -967.55
 -968.14 -967.54 -968.22 -968.38 -966.84 -967.19 -968.83 -968.44 -969.46 -967.85
 -967.76 -970.99 -970.53 -971.34 -972.40 -971.30 -971.25 -970.78 -969.29 -969.19
 -969.61 -971.71 -971.83 -971.06 -973.69 -971.24 -970.11 -966.19 -965.14 -965.47
 -963.81 -958.17 -952.12 -942.81 -926.12 -917.08 -907.22 -883.65 -880.54 -879.24
 9444.25 9481.40 9538.79 9567.76 9588.14 9649.29 9733.88 9802.74 9853.10 9860.12
 9871.60 9914.24 9940.46 9983.27 9983.2710016.7310016.7310124.0810238.8410284.75
10301.4910376.5610403.3910460.1710498.2710512.6410527.0210529.7910541.3910555.76
10627.2410808.2310822.1610836.0810900.7111017.0711231.2811260.0211274.3911365.13
11379.0511406.9011420.8211434.7411475.6111489.9811518.2711576.2211601.8111619.34
11633.7111657.5011676.8311691.2011719.9511734.3211748.6911791.8111806.1811843.79
   51.59   47.20   44.71   44.84   46.57   50.01   48.05   44.45   40.10   39.99
   38.62   35.93   34.67   34.35   34.35   34.02   34.02   32.17   31.61   32.45
   31.86   32.46   31.78   31.62   33.16   32.81   31.17   31.56   30.54   32.15
   32.24   29.01   29.47   28.66   27.60   28.70   28.75   29.22   30.71   30.81
   30.39   28.29   28.17   28.94   26.31   28.76   29.89   33.81   34.86   34.53
   36.19   41.83   47.88   57.19   73.88   82.92   92.78  116.35  119.46  120.76
 -948.41 -952.80 -955.29 -955.16 -953.43 -949.99 -951.95 -955.55 -959.90 -960.01
 -961.38 -964.07 -965.33 -965.65   31.85   31.52 -965.98 -967.83 -968.39 -967.55
 -968.14 -967.54 -968.22 -968.38 -966.84 -967.19 -968.83 -968.44 -969.46 -967.85
 -967.76 -970.99 -970.53 -971.34 -972.40 -971.30 -971.25 -970.78 -969.29 -969.19
 -969.61 -971.71 -971.83 -971.06 -973.69 -971.24 -970.11 -966.19 -965.14 -965.47
 -963.81 -958.17 -952.12 -942.81 -926.12 -917.08 -907.22 -883.65 -880.54 -879.24
Pier Skew, UpSta & Num, DnSta & Num=  ,10000.00, 2 ,10000.00, 2 , 0 , 0 , 0 ,,
    2.00    2.00
 -965.81   34.19
    2.00    2.00
 -965.81   34.19
BR Coef=-1 , 0 , 0 ,, 0 ,,,0.8,0,1,0,
WSPro=,,,, 1 ,,,, 0 ,,,, 0 ,,,,-1 ,-1 ,-1 , 0 , 0 , 0 , 0 , 0
BC Design=,, 0 ,, 0 ,,,,,,

Type RM Length L Ch R = 1 ,10932.16,619.161700,619.161700,619.161700
XS GIS Cut Line= 4
 392337.60500139852066.522386432392866.771668077852345.689053118
393172.988456875852552.424052939 395276.28706798  854657.3502682
#Sta/Elev= 30
9425.92553.598349572.682 51.33129649.10559.820419728.24959.237779841.31241.21973
9954.37532.638529965.68123.21767  9999.619.3344810046.2125.8908810094.4721.29843
10130.6730.39986   1019133.5901511471.7525.7410611627.3737.3398611698.11 71.8455
11768.58118.716111924.47131.808511966.92124.2436 12080.180.5437412094.24 69.8172
12122.5434.7377312136.6925.7612912207.4317.2146312292.3117.0693212447.1424.50405
13055.0228.6284913127.0236.3502813183.6151.2494313295.3464.2611513369.3565.74172
#Mann= 3 , 0 , 0
9425.925  0.0412       09425.925  0.0412       013369.35  0.0412       0
#XS Ineff= 2 , 0
       0                10462.69       0
Bank Sta=9425.925,13369.35
Exp/Cntr=0.3,0.1

Type RM Length L Ch R = 1 ,10312.99,474.952500,474.952500,474.952500
XS GIS Cut Line= 6
392238.131048107852650.776490138392739.250448531852787.193844323
392900.496075712 852948.65873134393695.967557044853386.387404725
394340.278153802853965.461376186395080.412402178854759.424645879
#Sta/Elev= 30
9375.099139.61139392.607146.24199428.215143.30979444.502136.49859465.261112.1415
9547.69791.806699599.213 58.73719671.33542.030799784.70328.732939936.72529.31619
 9996.5716.9406710041.9728.3545110286.8432.4245310527.4226.3744311038.0725.94836
11180.7629.9052811389.3525.8328611455.8742.8069311500.4964.7263611647.44113.2157
11758.89111.922311856.7950.6972811884.7625.6884811947.7116.5952711998.0823.47006
12240.3823.3706112282.02  19.27112609.5124.7406212698.41 39.298712991.7557.30735
#Mann= 3 , 0 , 0
9375.099  0.0652       09375.099  0.0652       012991.75  0.0652       0
#XS Ineff= 2 , 0
       0                10238.71       0
Bank Sta=9375.099,12991.75
Exp/Cntr=0.3,0.1

Type RM Length L Ch R = 1 ,9838.042,474.952600,474.952600,474.952600
XS GIS Cut Line= 6
391760.219866186852967.671786996392644.352399368853219.506931801
392795.612426282853338.603946286393443.790726725853563.544292076
393952.141565882853942.948629109394741.633833024854757.717633067
#Sta/Elev= 30
8967.619113.57679016.415108.53539038.20985.695479092.67251.443349124.87239.14884
9241.91217.360269399.12119.892389450.99126.718569502.38248.153099584.281103.7261
 9614.87111.85719726.687 56.76459859.48829.046539966.04626.01588    999916.14902
10027.8917.4078810052.4227.2701210427.7830.5801211350.2122.0436811498.2133.67458
11525.42 53.170511533.7953.2242211622.3236.2227311897.7415.1272311911.4920.28916
12144.59 23.794412241.4723.1537212261.1616.63855 12392.339.3619712547.6855.86171
#Mann= 3 , 0 , 0
8967.619    0.06       08967.619    0.06       012547.68    0.06       0
#XS Ineff= 2 , 0
       09627.397        10227.61       0
Bank Sta=8967.619,12547.68
Exp/Cntr=0.3,0.1

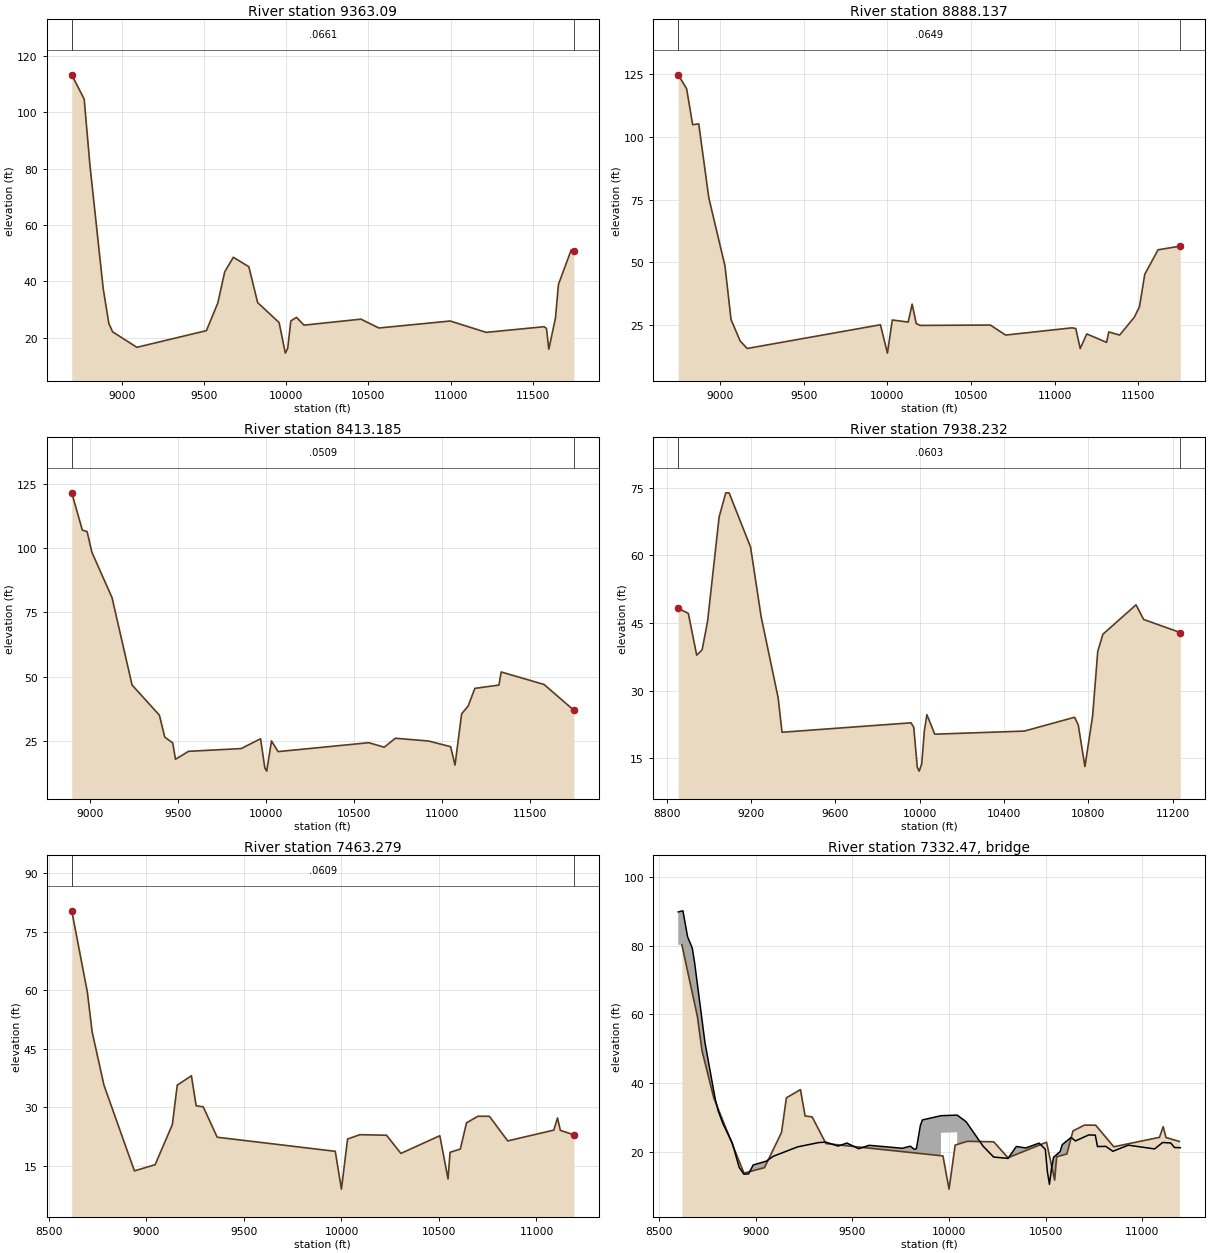
Type RM Length L Ch R = 1 , 9363.09,474.952600,474.952600,474.952600
XS GIS Cut Line= 6
391570.239465227853153.128631215392148.368945598853462.756143428
392620.811333603853635.543372841393148.709133958853953.910076588
393601.999328618854309.092575497394098.897915401854806.749206871
#Sta/Elev= 30
8694.016113.37468769.566104.75838804.56481.272958885.39737.443888919.75425.02539
 8942.5822.063019090.25516.552149513.87222.47935 9583.2432.309679625.26943.38372
9677.73148.550369772.16545.19401 9825.7732.435599956.49525.348439994.23714.48712
10008.6616.1464610027.8525.9204510062.1427.1982210107.8524.4295610454.7826.55907
10563.8223.4198210998.3825.8985611217.3721.8644111569.8523.8783611584.2523.27259
11598.5715.8910911639.1626.9997211657.2338.9082111734.8751.1608411750.9350.79211
#Mann= 3 , 0 , 0
8694.016  0.0661       08694.016  0.0661       011750.93  0.0661       0
#XS Ineff= 2 , 0
       09806.481        10371.28       0
Bank Sta=8694.016,11750.93
Exp/Cntr=0.3,0.1

Type RM Length L Ch R = 1 ,8888.137,474.952500,474.952500,474.952500
XS GIS Cut Line= 6
391493.469253137853228.071212799392054.573048703853609.678104042
392263.675031323853779.850586243392359.994510114853889.149309166
392636.687897286854297.790910647393548.992904406855375.274957881
#Sta/Elev= 30
8750.906124.83168801.014119.27658837.209104.91478873.405105.25448933.73175.68863
9030.25248.512249066.44727.114679120.75518.588169162.96915.585729959.013 25.0481
   1000113.7260210029.9826.94873 10124.9 26.124910148.63  33.28410173.0225.52022
 10197.624.78851 10615.824.93693 10707.120.9334511103.7123.82707 11126.423.55022
11152.7415.5645411192.2621.3787811310.4218.0285411323.4522.19268 11388.620.93707
11475.4628.0138811506.8332.2145311538.5445.1868611617.8154.9687511750.97 56.4472
#Mann= 3 , 0 , 0
8750.906  0.0649       08750.906  0.0649       011750.97  0.0649       0
#XS Ineff= 2 , 0
       09720.852         11223.6       0
Bank Sta=8750.906,11750.97
Exp/Cntr=0.3,0.1

Type RM Length L Ch R = 1 ,8413.185,474.952600,474.952600,474.952600
XS GIS Cut Line= 6
391350.398131324853439.071057758391600.277210649853676.242332933
391813.037371672853916.005441212392171.029420362854402.575436084
392768.739354316855185.035128329393124.892061629855668.142895567
#Sta/Elev= 30
8896.734121.54668956.853107.02228983.942106.44659011.08498.415249125.59180.73888
9239.53646.704069394.95134.934369425.27626.411489470.76524.125659486.37417.76349
9560.67720.860469859.80921.929039969.98825.754329994.47214.3489810005.0913.14657
10032.1424.9184810069.5120.7467510585.0124.2163910673.2222.4697110736.2225.95239
10924.8924.8759511050.3622.6664511075.4515.5288911113.0935.4344511150.7338.57651
11188.1445.3789411325.2846.6731911337.7551.7704411581.5446.9065211750.9836.86836
#Mann= 3 , 0 , 0
8896.734  0.0509       08896.734  0.0509       011750.98  0.0509       0
#XS Ineff= 2 , 0
       09470.918        11233.83       0
Bank Sta=8896.734,11750.98
Exp/Cntr=0.3,0.1

Type RM Length L Ch R = 1 ,7938.232,474.952500,474.952500,474.952500
XS GIS Cut Line= 6
391080.348082418853618.921044701 391468.73655225854122.390401635
391701.800050994854522.975677781391827.990126696854621.133837714
392026.323151185  854846.5211326392497.785995501855519.181268968
#Sta/Elev= 30
8853.86848.233458901.69647.15389 8941.4637.877198967.24139.061178993.02245.32165
9047.88168.495039079.576 73.86179095.42373.842639197.13361.841939247.42846.37989
 9327.7528.506479346.55720.790099958.95122.879539971.76321.867769988.53913.00351
9997.47112.1698810009.6213.7864910021.8221.0256310034.0224.6847210071.2820.36185
10496.3721.04502 10734.924.1082610752.4522.4218810784.0813.1840310820.5924.41623
10844.9338.7109910869.2742.5085311026.5949.0314811062.7945.7887911236.7642.89251
#Mann= 3 , 0 , 0
8853.868  0.0603       08853.868  0.0603       011236.76  0.0603       0
#XS Ineff= 2 , 0
       09319.616        10980.58       0
Bank Sta=8853.868,11236.76
Exp/Cntr=0.3,0.1

Type RM Length L Ch R = 1 ,7463.279,228.570500,228.570500,228.570500
XS GIS Cut Line= 4
390813.299445808853558.883497581391346.632779151854336.661275342
391679.966112494855364.439053103 391968.85500136855833.883497551
#Sta/Elev= 30
8616.961 80.30488697.129  59.4428721.37949.355068782.00535.689848938.25513.74406
 9044.3515.326569132.76325.586479157.88635.686229230.63838.086089254.88830.40003
9291.26430.137629362.63722.357239968.28418.750389999.8239.07468310031.3621.89415
10094.4423.00857 10231.122.8693910304.6918.2168910504.4422.7451510546.4911.69846
   1055718.5059410609.5619.3208610641.1726.0272810699.8827.7301910758.5927.71904
10852.5221.4180111088.9724.1773111108.0527.2822111122.59 24.117211191.7222.97769
#Mann= 3 , 0 , 0
8616.961  0.0609       08616.961  0.0609       011191.72  0.0609       0
#XS Ineff= 2 , 0
       09286.396        10727.99       0
Bank Sta=8616.961,11191.72
Exp/Cntr=0.3,0.1

Type RM Length L Ch R = 3 , 7332.47,,,
BEGIN DESCRIPTION:
END DESCRIPTION:
Bridge Culvert--1,0,-1,-1, 0
Deck Dist Width WeirC Skew NumUp NumDn MinLoCord MaxHiCord MaxSubmerge Is_Ogee
92.139650,44.291200,2.6,0, 60, 60, , , 0.95, 0, 0,0,,
 8598.12 8622.43 8646.68 8670.94 8683.06 8736.27 8789.31 8804.33 8828.58 8877.71
 8913.46 8937.71 8961.97 8986.22 9054.50 9089.86 9216.62 9325.75 9362.13 9425.77
 9471.27 9531.85 9586.43 9757.86 9799.52 9820.34 9830.76 9851.58 9862.00 9958.17
 9958.1710041.8310041.8310088.0310175.2710230.7410305.0910347.9710397.1510465.91
10498.0710508.7910519.5110530.2310540.9510574.6010585.9810631.4910654.2510722.51
10756.6410768.0210811.5610847.6710927.3111063.8411105.0811147.0111166.2411196.76
   89.88   90.20   82.62   79.32   75.00   51.87   35.43   32.01   28.27   22.55
   15.44   13.43   13.51   16.12   17.23   18.65   21.40   22.65   22.78   21.63
   22.51   20.85   21.85   20.99   21.59   20.67   20.88   27.68   29.25   30.48
   30.48   30.65   30.65   28.74   21.65   18.42   18.03   21.50   21.08   22.48
   20.68   14.12   10.48   15.20   18.39   20.01   22.05   24.14   23.12   24.87
   24.81   21.49   21.53   20.10   21.89   20.80   22.66   22.54   21.21   21.15
 -910.12 -909.80 -917.38 -920.68 -925.00 -948.13 -964.57 -967.99 -971.73 -977.45
 -984.56 -986.57 -986.49 -983.88 -982.77 -981.35 -978.60 -977.35 -977.22 -978.37
 -977.49 -979.15 -978.15 -979.01 -978.41 -979.33 -979.12 -972.32 -970.75 -969.52
   25.48   25.65 -969.35 -971.26 -978.35 -981.58 -981.97 -978.50 -978.92 -977.52
 -979.32 -985.88 -989.52 -984.80 -981.61 -979.99 -977.95 -975.86 -976.88 -975.13
 -975.19 -978.51 -978.47 -979.90 -978.11 -979.20 -977.34 -977.46 -978.79 -978.85
 8598.12 8622.43 8646.68 8670.94 8683.06 8736.27 8789.31 8804.33 8828.58 8877.71
 8913.46 8937.71 8961.97 8986.22 9054.50 9089.86 9216.62 9325.75 9362.13 9425.77
 9471.27 9531.85 9586.43 9757.86 9799.52 9820.34 9830.76 9851.58 9862.00 9958.17
 9958.1710041.8310041.8310088.0310175.2710230.7410305.0910347.9710397.1510465.91
10498.0710508.7910519.5110530.2310540.9510574.6010585.9810631.4910654.2510722.51
10756.6410768.0210811.5610847.6710927.3111063.8411105.0811147.0111166.2411196.76
   89.88   90.20   82.62   79.32   75.00   51.87   35.43   32.01   28.27   22.55
   15.44   13.43   13.51   16.12   17.23   18.65   21.40   22.65   22.78   21.63
   22.51   20.85   21.85   20.99   21.59   20.67   20.88   27.68   29.25   30.48
   30.48   30.65   30.65   28.74   21.65   18.42   18.03   21.50   21.08   22.48
   20.68   14.12   10.48   15.20   18.39   20.01   22.05   24.14   23.12   24.87
   24.81   21.49   21.53   20.10   21.89   20.80   22.66   22.54   21.21   21.15
 -910.12 -909.80 -917.38 -920.68 -925.00 -948.13 -964.57 -967.99 -971.73 -977.45
 -984.56 -986.57 -986.49 -983.88 -982.77 -981.35 -978.60 -977.35 -977.22 -978.37
 -977.49 -979.15 -978.15 -979.01 -978.41 -979.33 -979.12 -972.32 -970.75 -969.52
   25.48   25.65 -969.35 -971.26 -978.35 -981.58 -981.97 -978.50 -978.92 -977.52
 -979.32 -985.88 -989.52 -984.80 -981.61 -979.99 -977.95 -975.86 -976.88 -975.13
 -975.19 -978.51 -978.47 -979.90 -978.11 -979.20 -977.34 -977.46 -978.79 -978.85
BR Coef=-1 , 0 , 0 ,, 0 ,,,0.8,0,1,0,
WSPro=,,,, 1 ,,,, 0 ,,,, 0 ,,,,-1 ,-1 ,-1 , 0 , 0 , 0 , 0 , 0
BC Design=,, 0 ,, 0 ,,,,,,

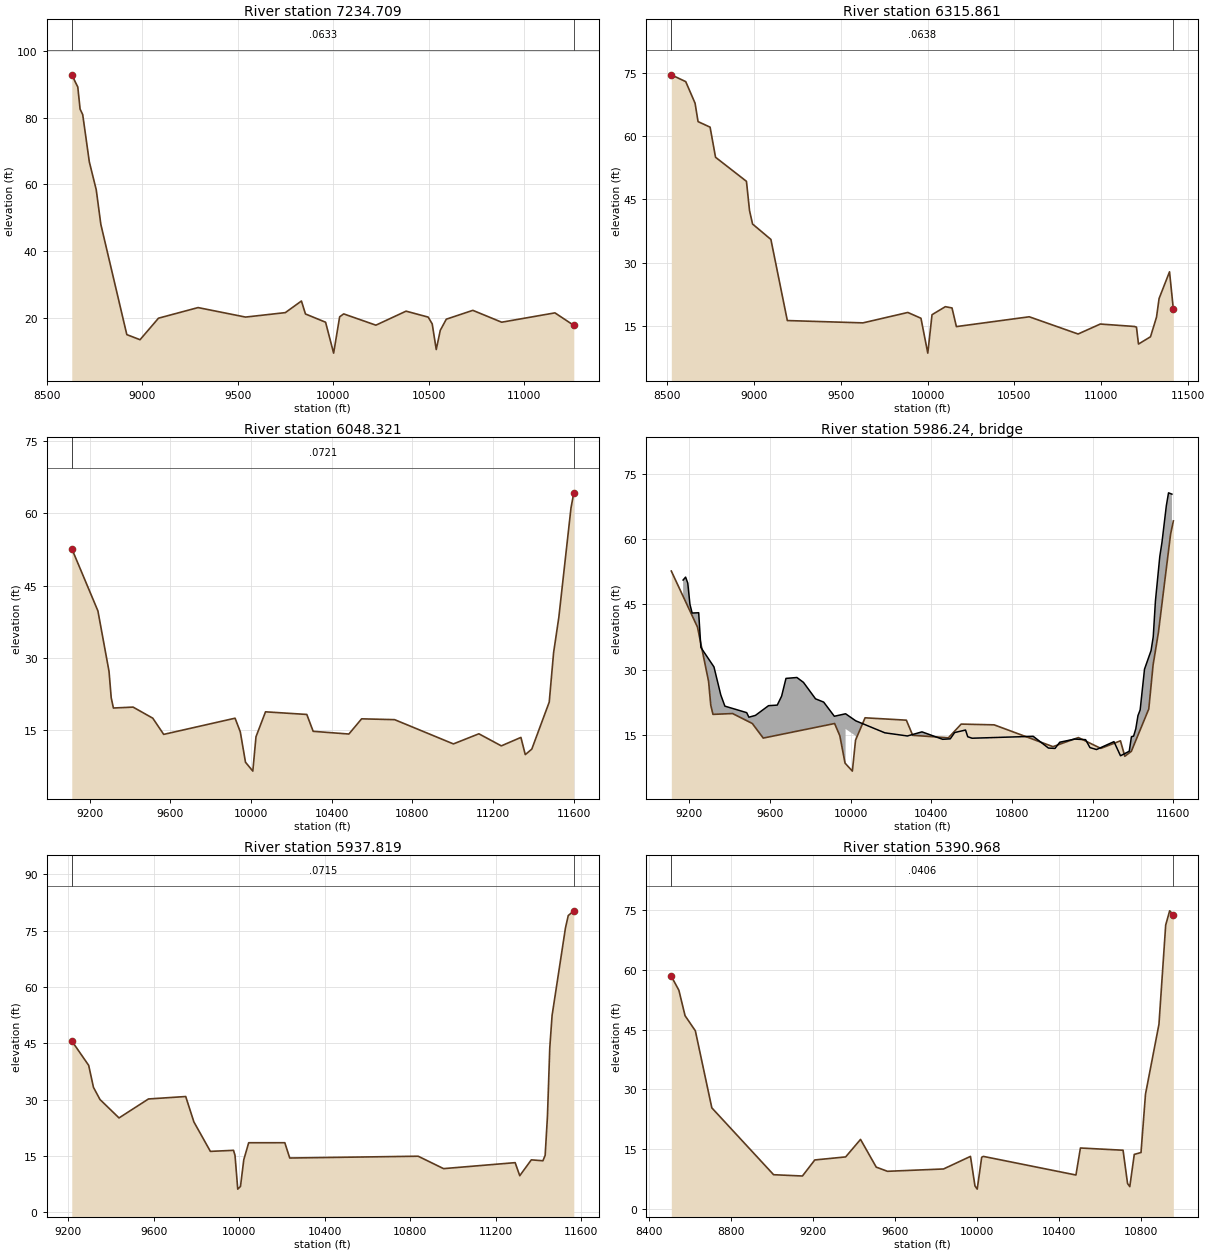
Type RM Length L Ch R = 1 ,7234.709,918.848300,918.848300,918.848300
XS GIS Cut Line= 4
390582.743890285853658.883497566391166.077223629854517.216830879
391463.299445838855400.550164223391802.188334733855969.994608656
#Sta/Elev= 30
8629.33392.79145 8660.9189.153878673.00182.533078686.71980.888178721.36466.74665
8757.637 58.39658781.81848.021438917.99915.029588987.362 13.50679084.08819.94968
9291.60423.124289540.67520.279719749.19521.614029833.60225.089019854.70421.21031
9960.21318.7403910002.429.48996310034.07 20.366610055.1721.2329710223.9917.85811
10382.2522.0520410498.3120.2727110519.4118.2244110540.5110.5569810561.6116.31549
10593.27 19.649810732.3122.2933510883.5918.7437111162.8721.5402411261.7817.79631
#Mann= 3 , 0 , 0
8629.333  0.0633       08629.333  0.0633       011261.78  0.0633       0
#XS Ineff= 2 , 0
       09281.075        10773.62       0
Bank Sta=8629.333,11261.78
Exp/Cntr=0.3,0.1

Type RM Length L Ch R = 1 ,6315.861,267.540000,267.540000,267.540000
XS GIS Cut Line= 6
389736.005029517853907.222915154390194.246449735 854568.21482176
390494.877196089  855067.1529981390647.910715745855257.502471611
390788.870342624855461.724567682 391305.98205168856328.890940037
#Sta/Elev= 30
8525.06874.532818608.12472.914488661.73867.807368679.03963.430648748.24362.12164
8779.68554.97242 8957.5849.264588975.16142.351698992.74239.135559098.27935.48012
9192.83816.238349628.15215.687729886.366 18.15859962.01116.7846810001.258.510927
10025.6817.6275810102.3919.5288310140.7519.2314410165.9514.8045410585.2817.13467
 10866.3 13.048410994.3215.4130511190.9114.8329411202.45 14.672411213.9910.66182
11283.2312.3917411317.8517.0564511332.5621.4616811392.6727.8033911414.67 18.9555
#Mann= 3 , 0 , 0
8525.068  0.0638       08525.068  0.0638       011414.67  0.0638       0
#XS Ineff= 2 , 0
       09412.308           11185       0
Bank Sta=8525.068,11414.67
Exp/Cntr=0.3,0.1

Type RM Length L Ch R = 1 ,6048.321,110.501800,110.501800,110.501800
XS GIS Cut Line= 4
389914.741929054  854314.5768307390212.050956845855022.042108476
390661.269706875 855390.96571961391093.127345741856447.823358491
#Sta/Elev= 30
9110.42752.71228 9240.15   39.799295.287 27.24819306.13421.768499316.98219.65148
9414.60619.83868 9512.2317.542489566.46614.180669920.46117.537819946.34114.72088
9972.2228.40606210008.546.55977910024.2913.6919110071.5618.86135 10276.418.31347
10307.9114.8166310485.0814.2539910548.2917.4084410711.9417.2357411003.6112.20425
 11129.914.3023311241.2711.8005911338.49 13.5517 11360.19.979464 11392.511.12921
11478.93 20.881211500.53 31.112711526.4538.4342111586.9561.1654711600.8164.28496
#Mann= 3 , 0 , 0
9110.427  0.0721       09110.427  0.0721       011600.81  0.0721       0
#XS Ineff= 2 , 0
       09883.164        11446.62       0
Bank Sta=9110.427,11600.81
Exp/Cntr=0.3,0.1

Type RM Length L Ch R = 3 , 5986.24,,,
BEGIN DESCRIPTION:
END DESCRIPTION:
Bridge Culvert--1,0,-1,-1, 0
Deck Dist Width WeirC Skew NumUp NumDn MinLoCord MaxHiCord MaxSubmerge Is_Ogee
39.174800,32.152200,2.6,0, 60, 60, , , 0.95, 0, 0,0,,
 9168.85 9181.29 9192.11 9202.94 9213.76 9246.24 9257.06 9322.01 9355.71 9376.14
 9484.39 9495.21 9527.69 9592.63 9635.93 9657.58 9679.23 9733.36 9765.83 9825.82
 9866.34 9919.05 9974.90 9974.9010025.1010025.1010169.3910281.6210353.8510456.48
10494.2110515.8710570.0010580.8210602.4810905.6210981.4011013.8811037.4511111.32
11165.4511187.1111219.5911306.2011338.6811381.9811392.8111403.6411414.4611425.29
11436.1211457.7711490.2511501.0711511.9011533.5511544.3811566.0311576.8611593.74
   50.64   51.32   49.92   45.00   43.03   43.10   35.09   30.60   24.16   21.55
   20.05   19.00   19.42   21.66   21.79   23.86   27.95   28.16   27.04   23.24
   22.48   19.22   19.79   19.79   18.17   18.17   15.40   14.67   15.62   13.90
   14.01   15.46   16.04   14.49   14.15   14.59   11.88   11.80   13.23   13.95
   13.82   11.99   11.54   13.36   10.10   11.15   14.48   14.64   16.32   19.37
   20.69   30.09   34.37   37.57   45.82   56.08   59.35   67.80   70.76   70.45
 -949.36 -948.68 -950.08 -955.00 -956.97 -956.90 -964.91 -969.40 -975.84 -978.45
 -979.95 -981.00 -980.58 -978.34 -978.21 -976.14 -972.05 -971.84 -972.96 -976.76
 -977.52 -980.78 -980.21   16.29   14.67 -981.83 -984.60 -985.33 -984.38 -986.10
 -985.99 -984.54 -983.96 -985.51 -985.85 -985.41 -988.12 -988.20 -986.77 -986.05
 -986.18 -988.01 -988.46 -986.64 -989.90 -988.85 -985.52 -985.36 -983.68 -980.63
 -979.31 -969.91 -965.63 -962.43 -954.18 -943.92 -940.65 -932.20 -929.24 -929.55
 9168.85 9181.29 9192.11 9202.94 9213.76 9246.24 9257.06 9322.01 9355.71 9376.14
 9484.39 9495.21 9527.69 9592.63 9635.93 9657.58 9679.23 9733.36 9765.83 9825.82
 9866.34 9919.05 9974.90 9974.9010025.1010025.1010169.3910281.6210353.8510456.48
10494.2110515.8710570.0010580.8210602.4810905.6210981.4011013.8811037.4511111.32
11165.4511187.1111219.5911306.2011338.6811381.9811392.8111403.6411414.4611425.29
11436.1211457.7711490.2511501.0711511.9011533.5511544.3811566.0311576.8611593.74
   50.64   51.32   49.92   45.00   43.03   43.10   35.09   30.60   24.16   21.55
   20.05   19.00   19.42   21.66   21.79   23.86   27.95   28.16   27.04   23.24
   22.48   19.22   19.79   19.79   18.17   18.17   15.40   14.67   15.62   13.90
   14.01   15.46   16.04   14.49   14.15   14.59   11.88   11.80   13.23   13.95
   13.82   11.99   11.54   13.36   10.10   11.15   14.48   14.64   16.32   19.37
   20.69   30.09   34.37   37.57   45.82   56.08   59.35   67.80   70.76   70.45
 -949.36 -948.68 -950.08 -955.00 -956.97 -956.90 -964.91 -969.40 -975.84 -978.45
 -979.95 -981.00 -980.58 -978.34 -978.21 -976.14 -972.05 -971.84 -972.96 -976.76
 -977.52 -980.78 -980.21   16.29   14.67 -981.83 -984.60 -985.33 -984.38 -986.10
 -985.99 -984.54 -983.96 -985.51 -985.85 -985.41 -988.12 -988.20 -986.77 -986.05
 -986.18 -988.01 -988.46 -986.64 -989.90 -988.85 -985.52 -985.36 -983.68 -980.63
 -979.31 -969.91 -965.63 -962.43 -954.18 -943.92 -940.65 -932.20 -929.24 -929.55
BR Coef=-1 , 0 , 0 ,, 0 ,,,0.8,0,1,0,
WSPro=,,,, 1 ,,,, 0 ,,,, 0 ,,,,-1 ,-1 ,-1 , 0 , 0 , 0 , 0 , 0
BC Design=,, 0 ,, 0 ,,,,,,

Type RM Length L Ch R = 1 ,5937.819,546.851000,546.851000,546.851000
XS GIS Cut Line= 4
389825.766234607854514.229608476390105.714151293855071.955302924
390572.294012427855445.219191819390999.811373502856489.055997387
#Sta/Elev= 30
9215.82745.637579295.01239.11209 9317.3933.254489347.86730.012579437.03225.10041
9574.738 30.15359749.11130.80631 9787.3324.046679864.56716.181659972.80516.46218
9979.82315.119859992.6296.11881210005.446.82879510020.83 13.946610043.8518.48359
10212.9218.4880710235.9514.4116410836.9814.8921410955.8411.5841211290.8413.17736
11312.459.69815211366.4813.9236811420.7613.6770311431.3215.1233511442.1225.59751
11452.9343.7928611463.7452.41284 11526.3 75.736511539.3879.0462711565.3780.31028
#Mann= 3 , 0 , 0
9215.827  0.0715       09215.827  0.0715       011565.37  0.0715       0
#XS Ineff= 2 , 0
       0                11388.63       0
Bank Sta=9215.827,11565.37
Exp/Cntr=0.3,0.1

Type RM Length L Ch R = 1 ,5390.968,646.237700,646.237700,646.237700
XS GIS Cut Line= 3
389633.946243372854178.225387981389720.098241982855070.670093332
390352.318266453856489.112608601
#Sta/Elev= 30
8509.89458.38452 8546.8454.870768576.97948.481348627.21244.680288707.58325.32137
9008.9788.5186559149.6298.1907069209.90812.224869360.60512.993259433.12517.39345
9509.76310.424369564.5059.3741949838.2139.9601459969.59313.12397 9991.495.703719
10002.444.89494210024.3312.9073910032.6213.1204710484.178.44181410506.0615.23097
10714.0814.6694510735.986.30851810746.935.51873110768.8213.6225310801.67 14.0971
10823.5628.7655810889.2546.32775 10922.1 71.266510941.4774.8355910959.4573.88306
#Mann= 3 , 0 , 0
8509.894  0.0406       08509.894  0.0406       010959.45  0.0406       0
#XS Ineff= 2 , 0
       09399.099                       0
Bank Sta=8509.894,10959.45
Exp/Cntr=0.3,0.1

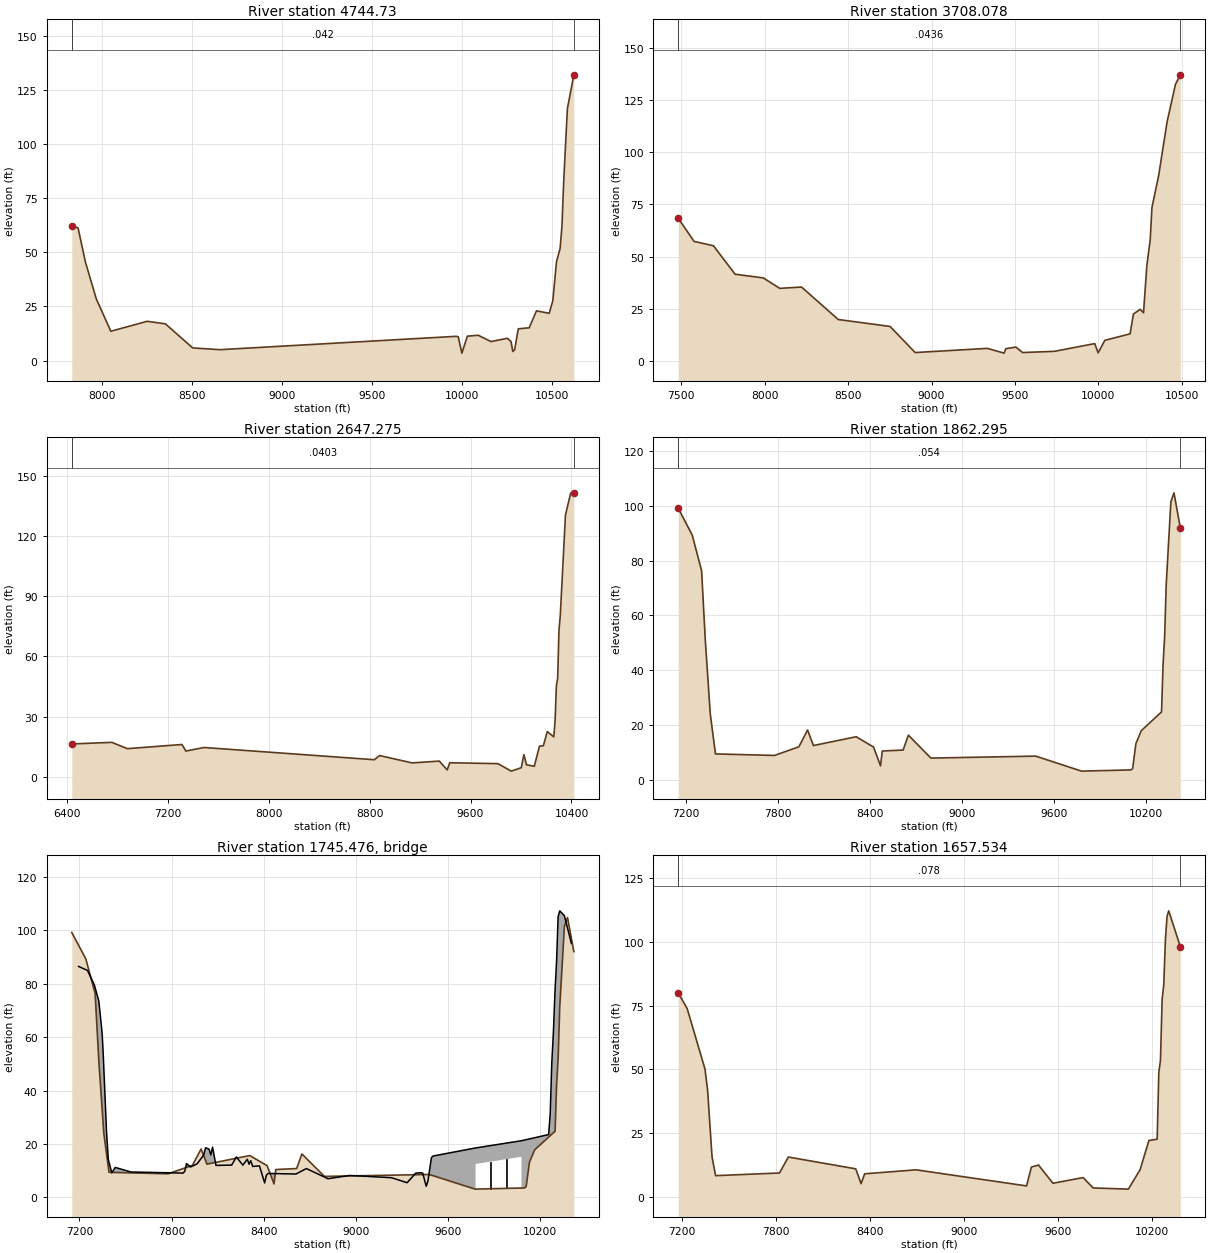
Type RM Length L Ch R = 1 , 4744.73,1036.652200,1036.652200,1036.652200
XS GIS Cut Line= 2
389205.206729183853850.258611146389617.293579742 856610.46719833
#Sta/Elev= 30
7829.36162.365397864.48761.31251 7904.9345.666287965.59528.534898046.48213.54398
8248.69918.154668349.80716.984358501.4695.8377618653.1325.030185 9967.5411.21497
9977.65110.956019997.8723.434611 10028.211.2789510088.8711.6930110159.658.786253
10250.6410.2906510270.868.78966510280.984.20394110291.094.98360510311.3114.66585
10371.9715.1580210412.4222.9845210483.1921.8502310503.4127.6926610523.64 45.6635
10543.8651.8680610553.9761.9926710564.0883.31374 10584.3116.483710620.16132.1364
#Mann= 3 , 0 , 0
7829.361   0.042       07829.361   0.042       010620.16   0.042       0
#XS Ineff= 2 , 0
       08991.628                       0
Bank Sta=7829.361,10620.16
Exp/Cntr=0.3,0.1

Type RM Length L Ch R = 1 ,3708.078,1060.803300,1060.803300,1060.803300
XS GIS Cut Line= 5
389112.335236743853683.186400642388673.897402058854262.495342366
388697.564190895854825.643154413388822.564190889 855957.58759882
388753.119746474856533.976487741
#Sta/Elev= 30
7481.527 68.31067576.535 57.25727692.529 55.17517822.41141.55446  7990.839.79652
8090.22334.78334 8220.5635.428948440.754 19.87098751.02816.575318901.8324.081174
9334.4466.0708489435.0543.8024039445.1155.9327059505.4796.6893989545.7234.076037
9736.8784.6732969978.4148.3604269998.5593.93375910038.85 9.9401410189.9313.01642
10210.0822.5056610250.3724.7473210270.5123.1081610290.6645.82802 10310.858.11113
10320.87 73.397110361.1688.6688610411.52114.330610461.89 132.37110491.07136.9369
#Mann= 3 , 0 , 0
7481.527  0.0436       07481.527  0.0436       010491.07  0.0436       0
#XS Ineff= 2 , 0
       0 8820.55                       0
Bank Sta=7481.527,10491.07
Exp/Cntr=0.3,0.1

Type RM Length L Ch R = 1 ,2647.275,784.979700,784.979700,784.979700
XS GIS Cut Line= 2
387101.094134092852427.341006883388053.568974606856289.425727625
#Sta/Elev= 30
6440.90416.329256757.781 17.11336881.37713.972697313.96116.04905 7344.8612.78064
7489.05514.554978838.3058.4630638879.50410.555899136.9946.8776029353.2867.785709
9415.0843.3909579435.6836.9602579816.7696.5065749923.5292.77671310002.164.473686
10022.7611.0151210043.365.95616610105.165.18829810146.3615.2261810177.2615.42243
10208.1622.5031710259.65 19.834610269.9527.6969610280.2545.1647710290.5549.11146
10300.8572.9087510311.15 80.274310352.35130.382310393.55 141.35310418.71141.4916
#Mann= 3 , 0 , 0
6440.904  0.0403       06440.904  0.0403       010418.71  0.0403       0
#XS Ineff= 2 , 0
       08758.173                       0
Bank Sta=6440.904,10418.71
Exp/Cntr=0.3,0.1

Type RM Length L Ch R = 1 ,1862.295,204.761000,204.761000,204.761000
XS GIS Cut Line= 4
385692.230354995853860.583775163386780.772021651855912.667108476
387413.584521651856160.062941805387457.855355024856425.687941819
#Sta/Elev= 30
7150.02899.192977241.29789.351397302.18576.365117326.65750.737637358.78423.99606
7392.7439.3875277777.6188.8305917936.09511.991997992.69418.119938030.869 12.4419
8309.64915.669518422.84811.891658468.1275.0289998479.44710.438698615.28510.80477
8649.722 16.25568796.4027.8635519479.3588.5839349778.127 3.0979110100.243.546621
10111.034.03656510132.4513.1855610167.5517.8833110299.3424.7396710309.4842.25285
10319.62 52.339110329.7571.2107510360.17101.489710380.44104.806310421.6992.05562
#Mann= 3 , 0 , 0
7150.028   0.054       07150.028   0.054       010421.69   0.054       0
#XS Ineff= 2 , 0
       08389.784                       0
Bank Sta=7150.028,10421.69
Exp/Cntr=0.3,0.1

Type RM Length L Ch R = 3 ,1745.476,,,
BEGIN DESCRIPTION:
END DESCRIPTION:
Bridge Culvert--1,0,-1,-1, 0
Deck Dist Width WeirC Skew NumUp NumDn MinLoCord MaxHiCord MaxSubmerge Is_Ogee
67.767700,69.225600,2.6,0, 60, 60, , , 0.95, 0, 0,0,,
 7194.37 7252.24 7297.52 7326.33 7347.67 7354.12 7376.76 7388.08 7410.73 7433.02
 7535.25 7874.86 7886.18 7897.50 7923.76 7966.43 8009.10 8022.02 8044.66 8055.98
 8067.30 8089.94 8191.83 8222.47 8265.14 8293.71 8305.03 8316.35 8329.15 8372.95
 8406.91 8418.23 8429.55 8610.68 8678.60 8819.90 8961.61 9233.29 9335.18 9391.78
 9425.74 9437.06 9459.70 9471.02 9493.66 9504.98 9781.56 9781.5610080.4410080.44
10257.4910267.7710278.0410288.3110298.5810308.8610319.1310329.4010360.2210405.64
   86.48   84.99   79.49   73.53   61.67   54.83   24.37   14.22    9.22   11.23
    9.52    9.10    9.74   12.69   11.39   12.55   15.80   18.59   18.06   15.90
   18.79   11.97   12.09   15.14   12.07   14.31   12.43   13.72   11.59   11.80
    5.42    8.32    8.98    8.75   10.80    6.99    8.22    7.37    5.50    9.10
    9.25    9.07    4.15    6.14   14.91   15.50   18.52   18.52   21.22   21.22
   23.53   31.40   50.49   61.66   76.89   88.06  105.03  107.30  105.49   95.08
 -913.52 -915.01 -920.51 -926.47 -938.33 -945.17 -975.63 -985.78 -990.78 -988.77
 -990.48 -990.90 -990.26 -987.31 -988.61 -987.45 -984.20 -981.41 -981.94 -984.10
 -981.21 -988.03 -987.91 -984.86 -987.93 -985.69 -987.57 -986.28 -988.41 -988.20
 -994.58 -991.68 -991.02 -991.25 -989.20 -993.01 -991.78 -992.63 -994.50 -990.90
 -990.75 -990.93 -995.85 -993.86 -985.09 -984.50 -981.48   12.52   15.22 -978.78
 -976.47 -968.60 -949.51 -938.34 -923.11 -911.94 -894.97 -892.70 -894.51 -904.92
 7194.37 7252.24 7297.52 7326.33 7347.67 7354.12 7376.76 7388.08 7410.73 7433.02
 7535.25 7874.86 7886.18 7897.50 7923.76 7966.43 8009.10 8022.02 8044.66 8055.98
 8067.30 8089.94 8191.83 8222.47 8265.14 8293.71 8305.03 8316.35 8329.15 8372.95
 8406.91 8418.23 8429.55 8610.68 8678.60 8819.90 8961.61 9233.29 9335.18 9391.78
 9425.74 9437.06 9459.70 9471.02 9493.66 9504.98 9861.86 9861.8610160.7510160.75
10257.4910267.7710278.0410288.3110298.5810308.8610319.1310329.4010360.2210405.64
   86.48   84.99   79.49   73.53   61.67   54.83   24.37   14.22    9.22   11.23
    9.52    9.10    9.74   12.69   11.39   12.55   15.80   18.59   18.06   15.90
   18.79   11.97   12.09   15.14   12.07   14.31   12.43   13.72   11.59   11.80
    5.42    8.32    8.98    8.75   10.80    6.99    8.22    7.37    5.50    9.10
    9.25    9.07    4.15    6.14   14.91   15.50   19.32   19.32   22.53   22.53
   23.53   31.40   50.49   61.66   76.89   88.06  105.03  107.30  105.49   95.08
 -913.52 -915.01 -920.51 -926.47 -938.33 -945.17 -975.63 -985.78 -990.78 -988.77
 -990.48 -990.90 -990.26 -987.31 -988.61 -987.45 -984.20 -981.41 -981.94 -984.10
 -981.21 -988.03 -987.91 -984.86 -987.93 -985.69 -987.57 -986.28 -988.41 -988.20
 -994.58 -991.68 -991.02 -991.25 -989.20 -993.01 -991.78 -992.63 -994.50 -990.90
 -990.75 -990.93 -995.85 -993.86 -985.09 -984.50 -980.68   13.32   16.53 -977.47
 -976.47 -968.60 -949.51 -938.34 -923.11 -911.94 -894.97 -892.70 -894.51 -904.92
Pier Skew, UpSta & Num, DnSta & Num=  ,9880.52, 2 ,9960.83, 2 , 0 , 0 , 0 ,,
    4.00    4.00
 -980.52   19.48
    4.00    4.00
 -979.82   20.18
Pier Skew, UpSta & Num, DnSta & Num=  ,9981.48, 2 ,10061.79, 2 , 0 , 0 , 0 ,,
    4.00    4.00
 -979.64   20.36
    4.00    4.00
 -978.94   21.06
BR Coef=-1 , 0 , 0 ,, 0 ,,,0.8,0,1,0,
WSPro=,,,, 1 ,,,, 0 ,,,, 0 ,,,,-1 ,-1 ,-1 , 0 , 0 , 0 , 0 , 0
BC Design=,, 0 ,, 0 ,,,,,,

Type RM Length L Ch R = 1 ,1657.534,903.354000,903.354000,903.354000
XS GIS Cut Line= 4
385577.647021681853954.333775163386692.230355024856063.708775148
387259.938688308856277.250441819387325.042855024856475.167108476
#Sta/Elev= 30
7177.60579.97495 7234.9173.737867348.01250.104247364.58341.959277393.25215.55777
7415.8738.2442187823.0399.284068 7879.59 15.55028309.37710.906628343.3075.104267
8365.9288.9648148693.92310.525339398.0364.2149449429.08411.617559474.32512.40876
9566.305 5.259319758.6187.4861089822.6493.41825610047.092.95395710121.8810.56281
10178.05 22.025510230.6822.5576210241.2148.7949410251.7453.4599410262.2677.27934
10272.7983.1979610283.32101.020810293.84110.072910304.37112.156110378.2498.14017
#Mann= 3 , 0 , 0
7177.605   0.078       07177.605   0.078       010378.24   0.078       0
#XS Ineff= 2 , 0
       08344.537                       0
Bank Sta=7177.605,10378.24
Exp/Cntr=0.3,0.1

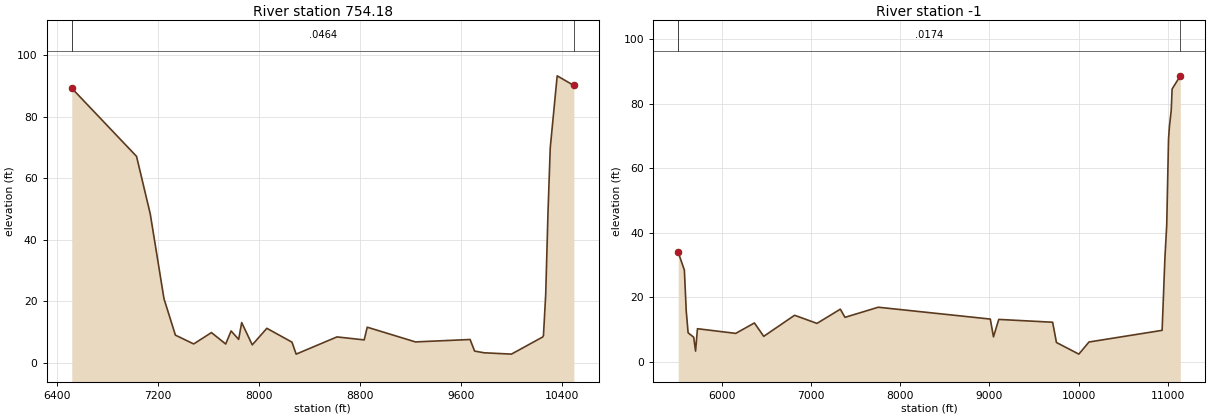
Type RM Length L Ch R = 1 ,  754.18,755.180000,755.180000,755.180000
XS GIS Cut Line= 2
384321.644811449853571.627181098386517.891428226856891.006729313
#Sta/Elev= 30
6514.57989.288827028.09367.127047136.82948.415327245.56420.857177336.1779.003362
7481.1586.1372657621.769 9.835747734.8756.1216617777.64910.373887837.6027.615799
7861.58413.088867945.5195.8401848061.08211.220938260.4316.7196998293.2492.828441
8616.9998.4270368832.8317.4520198856.81311.584979239.0526.7991879672.1817.585472
9708.1543.8172429782.7313.264934 10000.22.83331110247.748.40003610253.92 8.88845
10271.7222.2632210290.1649.3106510307.6969.9094610362.6593.3103710494.7590.17539
#Mann= 3 , 0 , 0
6514.579  0.0464       06514.579  0.0464       010494.75  0.0464       0
#XS Ineff= 2 , 0
       09057.233                       0
Bank Sta=6514.579,10494.75
Exp/Cntr=0.3,0.1

Type RM Length L Ch R = 1 ,      -1,0.000000,0.000000,0.000000
XS GIS Cut Line= 6
 382700.54593445853729.303700939383287.215643632855630.340842698
384428.714076345855867.890825715 385673.26334111856690.609816846
386405.902230006856978.804261263386586.457785553856961.443150245
#Sta/Elev= 30
5512.46933.944545581.22228.452295602.15315.832685623.0849.0489995685.8767.673648
5706.8063.3718645727.73710.312816156.8178.8625046366.12412.090466470.778 7.95006
6816.22214.469567067.30311.956897328.937 16.35617381.26413.830717754.00116.95771
9009.726 13.2965 9045.337.7951339104.67113.189129708.27612.314279751.0076.046726
10002.152.44233710115.716.19524110935.349.80303510966.9432.3599710987.0342.47694
11007.1268.9509411017.17 72.921111037.2677.8642811047.3184.5152811139.19 88.5871
#Mann= 3 , 0 , 0
5512.469  0.0174       05512.469  0.0174       011139.19  0.0174       0
#XS Ineff= 2 , 0
       09718.623                       0
Bank Sta=5512.469,11139.19
Exp/Cntr=0.3,0.1